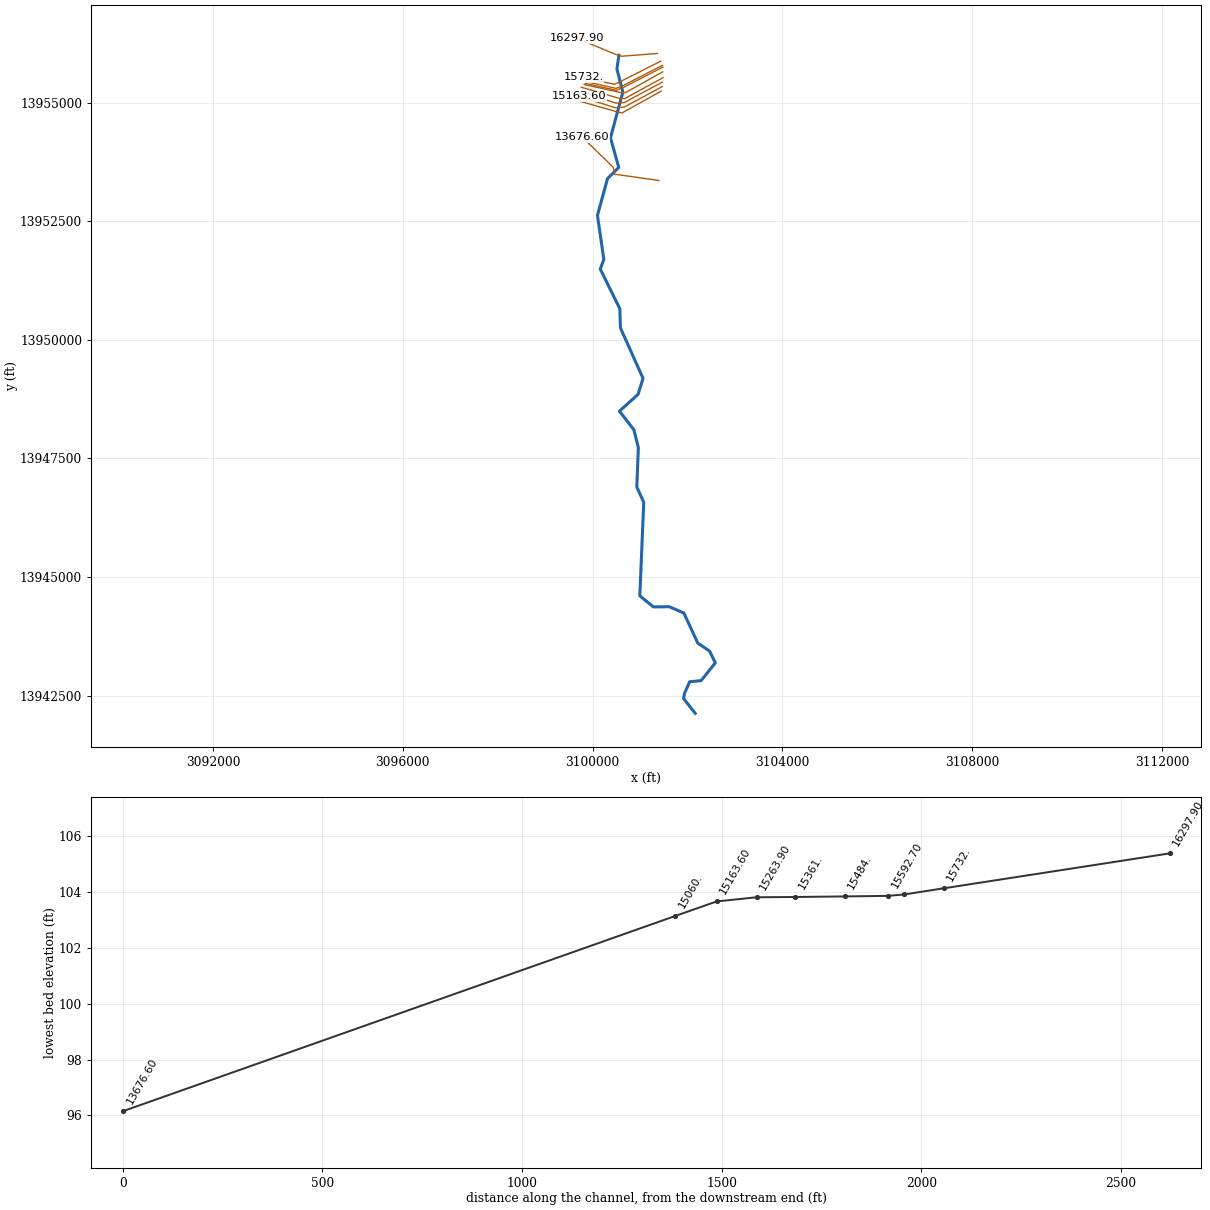
--- K120-00-00.prj (project) ---

Proj Title=K120-00-00
Current Plan=p02
Default Exp/Contr=.3,.1
English Units
Geom File=g01
Flow File=f02
Flow File=f01
Flow File=f04
Plan File=p02
Plan File=p01
Plan File=p04
Y Axis Title=Elevation
X Axis Title(PF)=Main Channel Distance
X Axis Title(XS)=Station
BEGIN DESCRIPTION:
Cypress Creek Watershed
Lemm Gully
HCFCD Unit K120-00-00
Flood Hazard Model
10, 2, 1, 0.2%
Filename k120-00-00
Prepared by:  Halff Associates  DATE:  03-26-04
Reviewed by:  _________  DATE:  __________________
STATUS (Final)
END DESCRIPTION:
DSS Export Rating Curves= 0
DSS Export Rating Curve Sorted= 0
DSS Export Volume Flow Curves= 0
DXF OffsetX= 0
DXF OffsetY= 0
DXF ScaleX= 1
DXF ScaleY= 10

--- K120-00-00.p02 (plan) ---

Plan Title=Floodway
Version=Version 3.0.1  Mar 2001
Short Identifier=Floodway0607
Geom File=g01
Flow File=f02
Subcritical Flow
K Sum by GR= 0
Std Step Tol= 0.01
Critical Tol= 0.01
Num of Std Step Trials= 20
Max Error Tol= 0.3
Flow Tol Ratio= 0.001
Split Flow NTrial= 30
Split Flow Tol= 0.02
Split Flow Ratio= 0.02
Log Output Level= 0
Friction Slope Method= 1
Unsteady Friction Slope Method= 2
Parabolic Critical Depth
Global Vel Dist= 0 , 0 , 0
Global Log Level= 0
CheckData=True
Encroach Param=-1 ,0,0, 3
Encroach River=K120-00-00
Encroach Reach=Reach - 1
Encroach Node=16297.90
       1  4978.4  5025.7       4       1
Encroach Node=15732.
       1  4965.4  5035.4       0       0       0
Encroach Node=15632.90
       1  4990.5  5011.7       4       1
Encroach Node=15612.80
       1  4990.5  5011.7       4       1
Encroach Node=15592.70
       1  4990.5  5011.7       4       1
Encroach Node=15484.
       1  4959.9  5059.9       0       0       0
Encroach Node=15361.
       1  4958.3  5048.3       0       0       0
Encroach Node=15263.90
       1  4944.9  5034.4       4       1
Encroach Node=15213.75
       1  4944.9  5034.4       4       1
Encroach Node=15163.60
       1  4944.9  5034.4       4       1
Encroach Node=15060.
       1  4967.3  5049.9       0       0       0
Encroach Node=13676.60
       1  4968.7  5040.6       4       1
Encroach Node=13330.
       1  4942.7  5042.2       0       0       0
Encroach Node=13233.60
       1  4960.9  5042.7       4       1
Encroach Node=13223.60
       1  4960.9  5042.7       4       1
Encroach Node=13213.60
       1  4959.9  5042.8       4       1
Encroach Node=13185.50
       1  4973.9  5065.2       4       1
Encroach Node=13058.10
       1  4973.9  5065.2       4       1
Encroach Node=12930.70
       1  4973.9  5065.2       4       1
Encroach Node=12832.
       1  4937.9  5048.2       0       0       0
Encroach Node=11782.60
       1  4960.2  5039.8       4       1
Encroach Node=11669.
       1  4942.2  5052.2       0       0       0
Encroach Node=11558.80
       1  4958.1  5037.7       4       1
Encroach Node=11547.80
       1  4961.3  5067.4       4       1
Encroach Node=11536.80
       1  4961.3  5067.4       4       1
Encroach Node=11427.
       1  4910.7  5061.8       0       0       0
Encroach Node=11164.70
       1  4937.9 5360.61       4       1
Encroach Node=10777.
       1  4930.3  5078.8       0       0       0
Encroach Node=10686.10
       1  4984.7  5014.7       4       1
Encroach Node=10659.50
       1  4984.7  5014.7       4       1
Encroach Node=10632.90
       1  4984.7  5014.7       4       1
Encroach Node=10520.
       1    4939  5079.3       0       0       0
Encroach Node=9867.
       1  4930.1    5068       0       0       0
Encroach Node=9710.30
       1 2659.91  2796.4       4       1
Encroach Node=9611.90
       1 2659.91  2796.4       4       1
Encroach Node=9513.50
       1 2659.91  2796.4       4       1
Encroach Node=9303.
       1    4932    5062       0       0       0
Encroach Node=7601.60
       1    4966  5038.2       4       1
Encroach Node=5849.00
       1  4961.8  5044.3       4       1
Encroach Node=4542.
       1  4940.5  5080.5       0       0       0
Encroach Node=4441.90
       1  4953.4  5050.6       4       1
Encroach Node=4418.30
       1  4953.4  5050.6       4       1
Encroach Node=4394.70
       1  4953.4  5050.6       4       1
Encroach Node=4294.
       1  4931.5  5071.5       0       0       0
Encroach Node=3707.20
       1  4945.4  5049.3       4       1
Encroach Node=2576.00
       1  4940.7  5035.3       4       1
Encroach Node=2462.
       1    4935  5059.5       0       0       0
Encroach Node=2362.40
       1    4963  5048.8       4       1
Encroach Node=2350.85
       1    4963  5048.8       4       1
Encroach Node=2339.30
       1    4963  5048.8       4       1
Encroach Node=2243
       1  4951.9  5051.9       0       0       0
Encroach Reach=K120-00-00_0022
Encroach Node=16297.90
       1  4978.4  5025.7       0       0       0
Encroach Node=15732.
       1  4965.4  5035.4       0       0       0
Encroach Node=15632.90
       1  4990.5  5011.7       0       0       0
Encroach Node=15612.80
       1  4990.5  5011.7       0       0       0
Encroach Node=15592.70
       1  4990.5  5011.7       0       0       0
Encroach Node=15484.
       1  4959.9  5059.9       0       0       0
Encroach Node=15361.
       1  4958.3  5048.3       0       0       0
Encroach Node=15263.90
       1  4944.9  5034.4       0       0       0
Encroach Node=15213.75
       1  4944.9  5034.4       0       0       0
Encroach Node=15163.60
       1  4944.9  5034.4       0       0       0
Encroach Node=15060.
       1  4967.3  5049.9       0       0       0
Encroach Node=13676.60
       1  4968.7  5040.6       0       0       0
Encroach Node=13330.
       1  4942.7  5042.2       0       0       0
Encroach Node=13233.60
       1  4960.9  5042.7       0       0       0
Encroach Node=13223.60
       1  4960.9  5042.7       0       0       0
Encroach Node=13213.60
       1  4959.9  5042.8       0       0       0
Encroach Node=13185.50
       1  4973.9  5065.2       0       0       0
Encroach Node=13058.10
       1  4973.9  5065.2       0       0       0
Encroach Node=12930.70
       1  4973.9  5065.2       0       0       0
Encroach Node=12832.
       1  4937.9  5048.2       0       0       0
Encroach Node=11782.60
       1  4960.2  5039.8       0       0       0
Encroach Node=11669.
       1  4942.2  5052.2       0       0       0
Encroach Node=11558.80
       1  4958.1  5037.7       0       0       0
Encroach Node=11547.80
       1  4961.3  5067.4       0       0       0
Encroach Node=11536.80
       1  4961.3  5067.4       0       0       0
Encroach Node=11427.
       1  4910.7  5061.8       0       0       0
Encroach Node=11164.70
       1  4937.9 5360.61       0       0       0
Encroach Node=10777.
       1  4930.3  5078.8       0       0       0
Encroach Node=10686.10
       1  4984.7  5014.7       0       0       0
Encroach Node=10659.50
       1  4984.7  5014.7       0       0       0
Encroach Node=10632.90
       1  4984.7  5014.7       0       0       0
Encroach Node=10520.
       1    4939  5079.3       0       0       0
Encroach Node=9867.
       1  4930.1    5068       0       0       0
Encroach Node=9710.30
       1 2659.91  2796.4       0       0       0
Encroach Node=9611.90
       1 2659.91  2796.4       0       0       0
Encroach Node=9513.50
       1 2659.91  2796.4       0       0       0
Encroach Node=9303.
       1    4932    5062       0       0       0
Encroach Node=7601.60
       1    4966  5038.2       0       0       0
Encroach Node=5849.00
       1  4961.8  5044.3       0       0       0
Encroach Node=4542.
       1  4940.5  5080.5       0       0       0
Encroach Node=4441.90
       1  4953.4  5050.6       0       0       0
Encroach Node=4418.30
       1  4953.4  5050.6       0       0       0
Encroach Node=4394.70
       1  4953.4  5050.6       0       0       0
Encroach Node=4294.
       1  4931.5  5071.5       0       0       0
Encroach Node=3707.20
       1  4945.4  5049.3       0       0       0
Encroach Node=2576.00
       1  4940.7  5035.3       0       0       0
Encroach Node=2462.
       1    4935  5059.5       0       0       0
Encroach Node=2362.40
       1    4963  5048.8       0       0       0
Encroach Node=2350.85
       1    4963  5048.8       0       0       0
Encroach Node=2339.30
       1    4963  5048.8       0       0       0
Encroach Node=2243
       1  4951.9  5051.9       0       0       0
Computation Interval=1HOUR
Output Interval=1HOUR
Run HTab= 0
Run UNet= 0
Run PostProcess= 0
UNET Theta= 1
UNET ZTol= 0.02
UNET ZSATol= 0.1
UNET MxIter= 20
UNET MaxInSteps= 20
UNET DtIC= 0
UNET DtMin= 0
UNET MaxCRTS= 20
UNET WFStab= 2
UNET SFStab= 1
UNET WFX= 1
UNET SFX= 1
UNET Convert EG Bridges=-1
UNET Use Existing IB Tables=-1
Instantaneous Interval=1HOUR
Write IC File= 0
Write Velocity= 0
Write Detailed= 0

--- K120-00-00.p01 (plan) ---

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Plan Title=FEMA Effective June 2007
Short Identifier=FEMAeff0607
Geom File=g01
Flow File=f01
Persistent XS Scale= 4902.95358649789 , 5084.38818565401 , 119.924050632911 , 102.759493670886 , 50 , 2
Encroach Param=-1 ,0,0, 0
IC Time=0

--- K120-00-00.p04 (plan) ---

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Plan Title=Storage Routing
Short Identifier=Store_Rout
Geom File=g01
Flow File=f04
Encroach Param=-1 ,0,0, 0

--- K120-00-00.f02 (steady flow) ---

Flow Title=Floodway
Version=Version 3.0.1  Mar 2001
Number of Profiles= 2
Profile Names=1PCT_100yr, 1PCTFloodway_100yrFW
River Rch & RM=K120-00-00,K120-00-00_0022,16297.90
     510     510
River Rch & RM=K120-00-00,K120-00-00_0022,15592.70
     530     530
River Rch & RM=K120-00-00,K120-00-00_0022,15163.60
     610     610
River Rch & RM=K120-00-00,K120-00-00_0022,13676.6
     660     660
River Rch & RM=K120-00-00,K120-00-00_0022,12930.70
     760     760
River Rch & RM=K120-00-00,K120-00-00_0022,11164.7
    1790    1790
River Rch & RM=K120-00-00,K120-00-00_0022,9513.50
    1900    1900
River Rch & RM=K120-00-00,K120-00-00_0022,7601.6
    2000    2000
River Rch & RM=K120-00-00,K120-00-00_0022,5849
    2060    2060
River Rch & RM=K120-00-00,K120-00-00_0022,4394.70
    2090    2090
River Rch & RM=K120-00-00,K120-00-00_0022,3707.2
    2140    2140
River Rch & RM=K120-00-00,K120-00-00_0022,2576.0
    2150    2150
River Rch & RM=K120-00-00,K120-00-00_0022,2339.30
    2254    2254
Boundary for River Rch & Prof#=K120-00-00,K120-00-00_0022, 1
Up Type= 0
Dn Type= 3
Dn Slope=.005
Boundary for River Rch & Prof#=K120-00-00,K120-00-00_0022, 2
Up Type= 0
Dn Type= 1
Dn Known WS=81.77
DSS Import GetInterval= 0
DSS Import GetPeak= 0
DSS Import FillOption= 0

--- K120-00-00.f01 (steady flow) ---

Flow Title=FEMA Effective June 2007
Version=Version 3.0.1  Mar 2001
Number of Profiles= 4
Profile Names=10PCT_10yr, 2PCT_50yr, 1PCT_100yr, 0.2PCT_500yr
River Rch & RM=K120-00-00,K120-00-00_0022,16297.90
     270     410     510     740
River Rch & RM=K120-00-00,K120-00-00_0022,15592.70
     280     430     530     770
River Rch & RM=K120-00-00,K120-00-00_0022,15163.60
     320     510     610     910
River Rch & RM=K120-00-00,K120-00-00_0022,13676.60
     350     550     660     990
River Rch & RM=K120-00-00,K120-00-00_0022,12930.70
     400     640     760    1150
River Rch & RM=K120-00-00,K120-00-00_0022,11164.70
     930    1560    1790    2550
River Rch & RM=K120-00-00,K120-00-00_0022,9513.50
     990    1630    1900    2720
River Rch & RM=K120-00-00,K120-00-00_0022,7601.60
    1050    1700    2000    2900
River Rch & RM=K120-00-00,K120-00-00_0022,5849.00
    1090    1750    2060    3000
River Rch & RM=K120-00-00,K120-00-00_0022,4394.70
    1100    1770    2090    3040
River Rch & RM=K120-00-00,K120-00-00_0022,3707.20
    1130    1810    2140    3120
River Rch & RM=K120-00-00,K120-00-00_0022,2576.00
    1140    1810    2150    3140
River Rch & RM=K120-00-00,K120-00-00_0022,2339.30
    1205    1895    2254    3311
Boundary for River Rch & Prof#=K120-00-00,K120-00-00_0022, 1
Up Type= 0
Dn Type= 3
Dn Slope=.005
Boundary for River Rch & Prof#=K120-00-00,K120-00-00_0022, 2
Up Type= 0
Dn Type= 3
Dn Slope=.005
Boundary for River Rch & Prof#=K120-00-00,K120-00-00_0022, 3
Up Type= 0
Dn Type= 3
Dn Slope=.005
Boundary for River Rch & Prof#=K120-00-00,K120-00-00_0022, 4
Up Type= 0
Dn Type= 3
Dn Slope=.005
DSS Import GetInterval= 0
DSS Import GetPeak= 0
DSS Import FillOption= 0

--- K120-00-00.f04 (steady flow) ---

Flow Title=Storage Routing
Version=Version 3.0.1  Mar 2001
Number of Profiles= 7
Profile Names=0.25*10% flood, 0.50*10%flood, 10% flood, 2% flood, 1% flood, 0.2%flood, 1.25*0.2% flood
River Rch & RM=K120-00-00,K120-00-00_0022,16297.90
      79     159     317     719     941    1541    1926
River Rch & RM=K120-00-00,K120-00-00_0022,15263.90
     113     226     451    1052    1383    2307    2884
River Rch & RM=K120-00-00,K120-00-00_0022,11782.6
     135     269     538    1270    1672    2808    3510
River Rch & RM=K120-00-00,K120-00-00_0022,11164.7
     299     598    1195    2667    3399    5533    6916
River Rch & RM=K120-00-00,K120-00-00_0022,10686.10
     315     631    1261    2779    3533    5760    7200
River Rch & RM=K120-00-00,K120-00-00_0022,9710.30
     338     675    1350    2929    3715    6066    7583
River Rch & RM=K120-00-00,K120-00-00_0022,5849
     367     734    1467    3129    3950    6471    8089
River Rch & RM=K120-00-00,K120-00-00_0022,4441.90
     369     738    1475    3143    3967    6499    8124
River Rch & RM=K120-00-00,K120-00-00_0022,3707.2
     382     764    1528    3234    4076    6684    8355
Boundary for River Rch & Prof#=K120-00-00,K120-00-00_0022, 1
Up Type= 0
Dn Type= 3
Dn Slope=.005
Boundary for River Rch & Prof#=K120-00-00,K120-00-00_0022, 2
Up Type= 0
Dn Type= 3
Dn Slope=.005
Boundary for River Rch & Prof#=K120-00-00,K120-00-00_0022, 3
Up Type= 0
Dn Type= 3
Dn Slope=.005
Boundary for River Rch & Prof#=K120-00-00,K120-00-00_0022, 4
Up Type= 0
Dn Type= 3
Dn Slope=.005
Boundary for River Rch & Prof#=K120-00-00,K120-00-00_0022, 5
Up Type= 0
Dn Type= 3
Dn Slope=.005
Boundary for River Rch & Prof#=K120-00-00,K120-00-00_0022, 6
Up Type= 0
Dn Type= 3
Dn Slope=.005
Boundary for River Rch & Prof#=K120-00-00,K120-00-00_0022, 7
Up Type= 0
Dn Type= 3
Dn Slope=.005
DSS Import GetInterval= 0
DSS Import GetPeak= 0
DSS Import FillOption= 0

--- K120-00-00.g01 (geometry) ---

Geom Title=K120-00-00 June 2007
Version=Version 3.0.1  Mar 2001

River Reach=K120-00-00      ,K120-00-00_0022
Reach XY= 30
      3100554.43     13955996.16      3100511.46     13955707.43
       3100636.6     13955219.71      3100375.99     13954257.78
      3100550.47     13953631.91      3100314.25     13953398.08
      3100101.57     13952621.17      3100236.12     13951694.52
      3100161.25     13951490.53      3100573.58     13950652.86
       3100586.6     13950248.12      3101061.86     13949188.01
      3100958.78     13948851.64      3100565.98     13948495.74
      3100868.72     13948104.03      3100963.66     13947725.66
      3100930.57     13946898.52        3101077.       13946574.
      3100994.59     13944603.59      3101281.04      13944370.3
      3101617.41     13944374.64        3101922.       13944242.
      3102216.26     13943607.61       3102465.4     13943439.21
      3102585.02     13943190.92      3102286.58     13942816.81
      3102044.39     13942793.37      3101938.49     13942552.05
      3101915.92     13942440.94      3102162.45      13942126.7

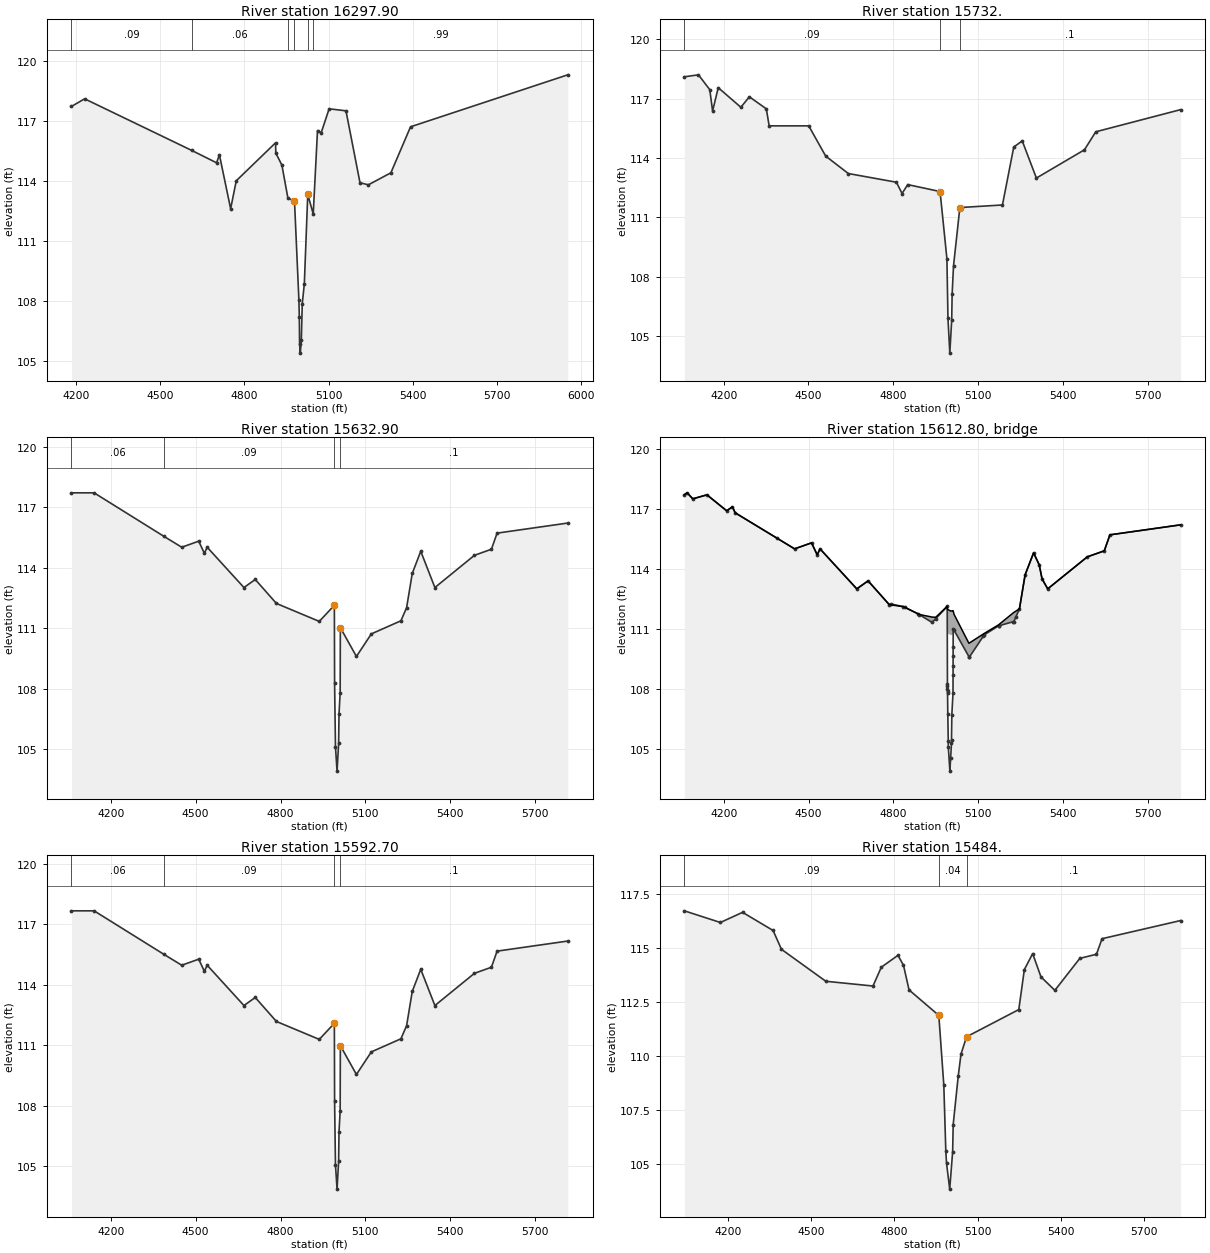
Type RM Length L Ch R = 1 ,16297.90,538,565.9,588
BEGIN DESCRIPTION:
Cross Section K120-00-00-X08
END DESCRIPTION:
XS GIS Cut Line= 4
      3101363.51      13956034.4      3100611.11     13955975.53
      3100502.68     13956007.33      3099671.82      13956353.1
#Sta/Elev= 30
  4184.1  117.72    4231   118.1  4612.2  115.52    4701   114.9    4711   115.3
    4751   112.6    4771     114    4911   115.9  4911.9  115.39  4933.6  114.78
  4955.2  113.12  4978.4     113  4994.2  108.02  4995.6   107.2  4996.6  105.84
  4999.1  105.38  5002.8  106.03  5006.1  107.85  5013.5  108.85  5025.7  113.32
  5045.2  112.34  5060.4  116.51  5073.5   116.4  5101.8   117.6  5161.8   117.5
  5211.8   113.9  5241.8   113.8  5321.8   114.4  5391.8   116.7  5951.8   119.3
#Mann= 6 ,-1 , 0
  4184.1     .09       0  4612.2     .06       0  4955.2    .045       0
  4978.4     .04       0  5025.7    .045       0  5045.2     .99       0
Bank Sta=4978.4,5025.7
XS Rating Curve= 0
Exp/Cntr=.3,.1

Type RM Length L Ch R = 1 ,15732.  ,101,99.1,96
BEGIN DESCRIPTION:
interpolated channel - LIDAR overbanks
WOOD BRIDGE 350' US LOUETTA - XS4
END DESCRIPTION:
XS GIS Cut Line= 5
      3101436.46     13955871.98      3100628.93     13955464.83
      3100551.97     13955422.63      3100456.94     13955383.24
      3099813.19     13955528.91
#Sta/Elev= 30
    4061   118.1    4111   118.2    4151  117.45    4161  116.37    4181  117.55
    4261  116.56    4291  117.09    4351  116.48    4361  115.62    4501  115.62
    4561  114.09    4641  113.21    4811  112.77    4831   112.2    4851  112.65
  4965.4   112.3 4989.64   108.9 4993.28   105.9 4999.87  104.13 5006.53   105.8
 5008.08  107.12 5012.95  108.54  5035.4  111.49    5186  111.62    5226  114.55
    5256  114.86    5306  112.98    5476  114.41    5516  115.32    5816  116.44
#Mann= 3 ,-1 , 0
    4061     .09       0  4965.4    .055       0  5035.4      .1       0
Bank Sta=4965.4,5035.4
XS Rating Curve= 0
Exp/Cntr=.5,.3

Type RM Length L Ch R = 1 ,15632.90,40.2,40.2,40.2
BEGIN DESCRIPTION:
Upstream Section of Bridge/Culvert/Weir
WOOD BRIDGE 350' US LOUETTA - XS 3
END DESCRIPTION:
XS GIS Cut Line= 5
      3101473.46      13955786.4      3100655.57     13955363.86
      3100601.72     13955343.67      3100493.95     13955297.66
       3099850.2      13955443.3
#Sta/Elev= 30
  4060.7  117.72  4140.7  117.72  4387.7  115.56  4450.7  115.02  4510.7  115.32
  4530.7  114.72  4540.7  115.02  4670.7  113.02  4710.7  113.42  4785.6  112.23
  4937.1  111.34  4990.5  112.14  4991.3  108.28  4994.4  105.12    5000  103.91
  5005.6   105.3  5006.9  106.74    5011   107.8  5011.7  111.03  5068.5   109.6
  5121.3  110.72  5225.9  111.37    5246  112.02    5266  113.72    5296  114.82
    5346  113.02    5486  114.62    5546  114.92    5566  115.72    5816  116.22
#Mann= 4 ,-1 , 0
  4060.7     .06       0  4387.7     .09       0  4990.5    .055       0
  5011.7      .1       0
#XS Ineff= 2 , 0
       0    4970  111.58    5030       0  110.28
Permanent Ineff=
       F       F
Bank Sta=4990.5,5011.7
XS Rating Curve= 0
Exp/Cntr=.5,.3

Type RM Length L Ch R = 3 ,15612.80,,,
BEGIN DESCRIPTION:
WOOD BRIDGE 350' US LOUETTA
Structure ID: K120-00-00-S4-1
END DESCRIPTION:
Bridge Culvert--1,0,-1,-1, 0
Deck Dist Width WeirC Skew NumUp NumDn MinLoCord MaxHiCord MaxSubmerge Is_Ogee
10,15,2.6,0, 42, 42, , , .95, 0, ,,,
  4060.7  4070.7  4090.7  4140.7  4210.7  4230.7  4240.7  4450.7  4510.7  4530.7
  4540.7  4670.7  4710.7  4785.6  4835.7    4892  4937.1  4949.9  4990.5  4991.3
 4991.51  4991.6  5002.7 5011.29  5011.4  5011.7  5014.9  5067.3  5068.5  5121.3
    5172  5225.9    5246    5266    5296    5316    5326    5346    5486    5546
    5566    5816
   117.7   117.8   117.5   117.7   116.9   117.1   116.8     115   115.3   114.7
     115     113   113.4  112.21  112.11  111.72  111.59  111.58  112.13  111.98
  111.98  111.98  111.89  111.91  111.91  111.89  111.72  110.28  110.29  110.77
   111.2  111.82     112   113.7   114.8   114.2   113.5     113   114.6   114.9
   115.7   116.2
   117.7   117.8   117.5   117.7   116.9   117.1   116.8     115   115.3   114.7
     115     113   113.4  112.21  112.11  111.71  111.32  111.51  112.12  108.26
  108.01  110.78  110.69  110.71  109.63  111.01  110.93  109.61  109.58   110.7
  111.15  111.35     112   113.7   114.8   114.2   113.5     113   114.6   114.9
   115.7   116.2
  4060.7  4070.7  4090.7  4140.7  4210.7  4230.7  4240.7  4450.7  4510.7  4530.7
  4540.7  4670.7  4710.7  4785.6  4835.7    4892  4937.1  4949.9  4990.5  4991.3
 4991.51  4991.6  5002.7 5011.29  5011.4  5011.7  5014.9  5067.3  5068.5  5121.3
    5172  5225.9    5246    5266    5296    5316    5326    5346    5486    5546
    5566    5816
   117.7   117.8   117.5   117.7   116.9   117.1   116.8     115   115.3   114.7
     115     113   113.4  112.21  112.11  111.72  111.59  111.58  112.13  111.98
  111.98  111.98  111.89  111.91  111.91  111.89  111.72  110.28  110.29  110.77
   111.2  111.82     112   113.7   114.8   114.2   113.5     113   114.6   114.9
   115.7   116.2
   117.7   117.8   117.5   117.7   116.9   117.1   116.8     115   115.3   114.7
     115     113   113.4  112.21  112.11  111.71  111.32  111.51  112.12  108.26
  108.01  110.78  110.69  110.71  109.63  111.01  110.93  109.61  109.58   110.7
  111.15  111.35     112   113.7   114.8   114.2   113.5     113   114.6   114.9
   115.7   116.2
BR Coef= 1 , 0 , 0 ,1.25, 0 ,,,.8,0,2,0,
WSPro=,,,, 1 ,,,, 0 ,,,, 0 ,,,,-1 ,-1 ,-1 , 0 , 0 , 0 , 0 , 0
BR U #Sta/Elev= 62
  4060.7   117.7  4070.7   117.8  4090.7   117.5  4140.7   117.7  4210.7   116.9
  4230.7   117.1  4240.7   116.8  4387.7  115.54  4450.7     115  4510.7   115.3
  4530.7   114.7  4540.7     115  4670.7     113  4710.7   113.4  4785.6  112.21
    4790  112.25  4835.7  112.11  4841.8  112.07  4887.5  111.75    4892  111.71
  4937.1  111.32  4949.9  111.51  4990.5  112.12  4991.3  108.26  4991.4  108.14
 4991.51  108.01  4991.6  107.91  4991.7  107.79  4992.6  106.73  4994.3  105.38
  4994.4   105.1    5000  103.89  5002.7  104.56  5005.6  105.28  5005.7  105.47
  5006.9  106.72    5011  107.78  5011.2   108.7 5011.29  109.12  5011.4  109.63
  5011.5  110.09  5011.7  111.01  5014.9  110.93  5067.3  109.61  5068.5  109.58
  5118.6  110.64  5121.3   110.7    5172  111.15  5172.1  111.15  5222.2  111.35
  5225.9  111.35  5232.9  111.58    5246     112    5266   113.7    5296   114.8
    5316   114.2    5326   113.5    5346     113    5486   114.6    5546   114.9
    5566   115.7    5816   116.2
BR U #Mann= 4
  4060.7     .06  4387.7     .09  4990.5    .055  5011.7      .1
BR D #Sta/Elev= 62
  4060.7   117.7  4070.7   117.8  4090.7   117.5  4140.7   117.7  4210.7   116.9
  4230.7   117.1  4240.7   116.8  4387.7  115.54  4450.7     115  4510.7   115.3
  4530.7   114.7  4540.7     115  4670.7     113  4710.7   113.4  4785.6  112.21
    4790  112.25  4835.7  112.11  4841.8  112.07  4887.5  111.75    4892  111.71
  4937.1  111.32  4949.9  111.51  4990.5  112.12  4991.3  108.26  4991.4  108.14
 4991.51  108.01  4991.6  107.91  4991.7  107.79  4992.6  106.73  4994.3  105.38
  4994.4   105.1    5000  103.89  5002.7  104.56  5005.6  105.28  5005.7  105.47
  5006.9  106.72    5011  107.78  5011.2   108.7 5011.29  109.12  5011.4  109.63
  5011.5  110.09  5011.7  111.01  5014.9  110.93  5067.3  109.61  5068.5  109.58
  5118.6  110.64  5121.3   110.7    5172  111.15  5172.1  111.15  5222.2  111.35
  5225.9  111.35  5232.9  111.58    5246     112    5266   113.7    5296   114.8
    5316   114.2    5326   113.5    5346     113    5486   114.6    5546   114.9
    5566   115.7    5816   116.2
BR D #Mann= 4
  4060.7     .06  4387.7     .09  4990.5    .055  5011.7      .1
BC Design=,, 0 ,, 0 ,,,,,,
BC HTab HWMax=117.82

Type RM Length L Ch R = 1 ,15592.70,124,108.7,84
BEGIN DESCRIPTION:
Downstream Section of Bridge/Culvert/Weir
WOOD BRIDGE 350' US LOUETTA - XS 2
END DESCRIPTION:
XS GIS Cut Line= 5
      3101483.37       13955749.      3100664.42     13955325.93
      3100609.88     13955305.48      3100496.58     13955257.11
      3099846.51      13955404.2
#Sta/Elev= 30
  4060.7  117.67  4140.7  117.67  4387.7  115.51  4450.7  114.97  4510.7  115.27
  4530.7  114.67  4540.7  114.97  4670.7  112.97  4710.7  113.37  4785.6  112.18
  4937.1  111.29  4990.5  112.09  4991.3  108.23  4994.4  105.07    5000  103.86
  5005.6  105.25  5006.9  106.69    5011  107.75  5011.7  110.98  5068.5  109.55
  5121.3  110.67  5225.9  111.32    5246  111.97    5266  113.67    5296  114.77
    5346  112.97    5486  114.57    5546  114.87    5566  115.67    5816  116.17
#Mann= 4 ,-1 , 0
  4060.7     .06       0  4387.7     .09       0  4990.5    .055       0
  5011.7      .1       0
#XS Ineff= 2 , 0
       0 4983.83  111.58 5018.37       0  110.28
Permanent Ineff=
       F       F
Bank Sta=4990.5,5011.7
XS Rating Curve= 0
Exp/Cntr=.5,.3

Type RM Length L Ch R = 1 ,15484.  ,124.6,123,107.7
BEGIN DESCRIPTION:
interpolated channel - LIDAR overbanks
WOOD BRIDGE 350' US LOUETTA - XS 1
END DESCRIPTION:
XS GIS Cut Line= 4
      3101476.43     13955647.25      3100684.62     13955204.32
      3100547.12     13955219.23      3099821.52     13955379.92
#Sta/Elev= 30
  4042.6  116.72  4172.6  116.18  4252.6  116.65  4362.6  115.81  4392.6  114.94
  4552.6  113.46  4722.6  113.24  4752.6  114.11  4812.6  114.66  4832.6   114.2
  4852.6  113.06  4959.9  111.88 4977.95  108.65 4985.17  105.59 4987.75  105.04
 4999.17  103.84 5009.71  105.56 5011.73  106.83  5029.9  109.07  5039.9  110.09
  5059.9  110.89  5248.2  112.15  5268.2     114  5298.2  114.74  5328.2  113.66
  5378.2  113.04  5468.2  114.52  5528.2  114.71  5548.2  115.43  5831.4  116.27
#Mann= 3 ,-1 , 0
  4042.6     .09       0  4959.9     .04       0  5059.9      .1       0
Bank Sta=4959.9,5059.9
XS Rating Curve= 0
Exp/Cntr=.3,.1

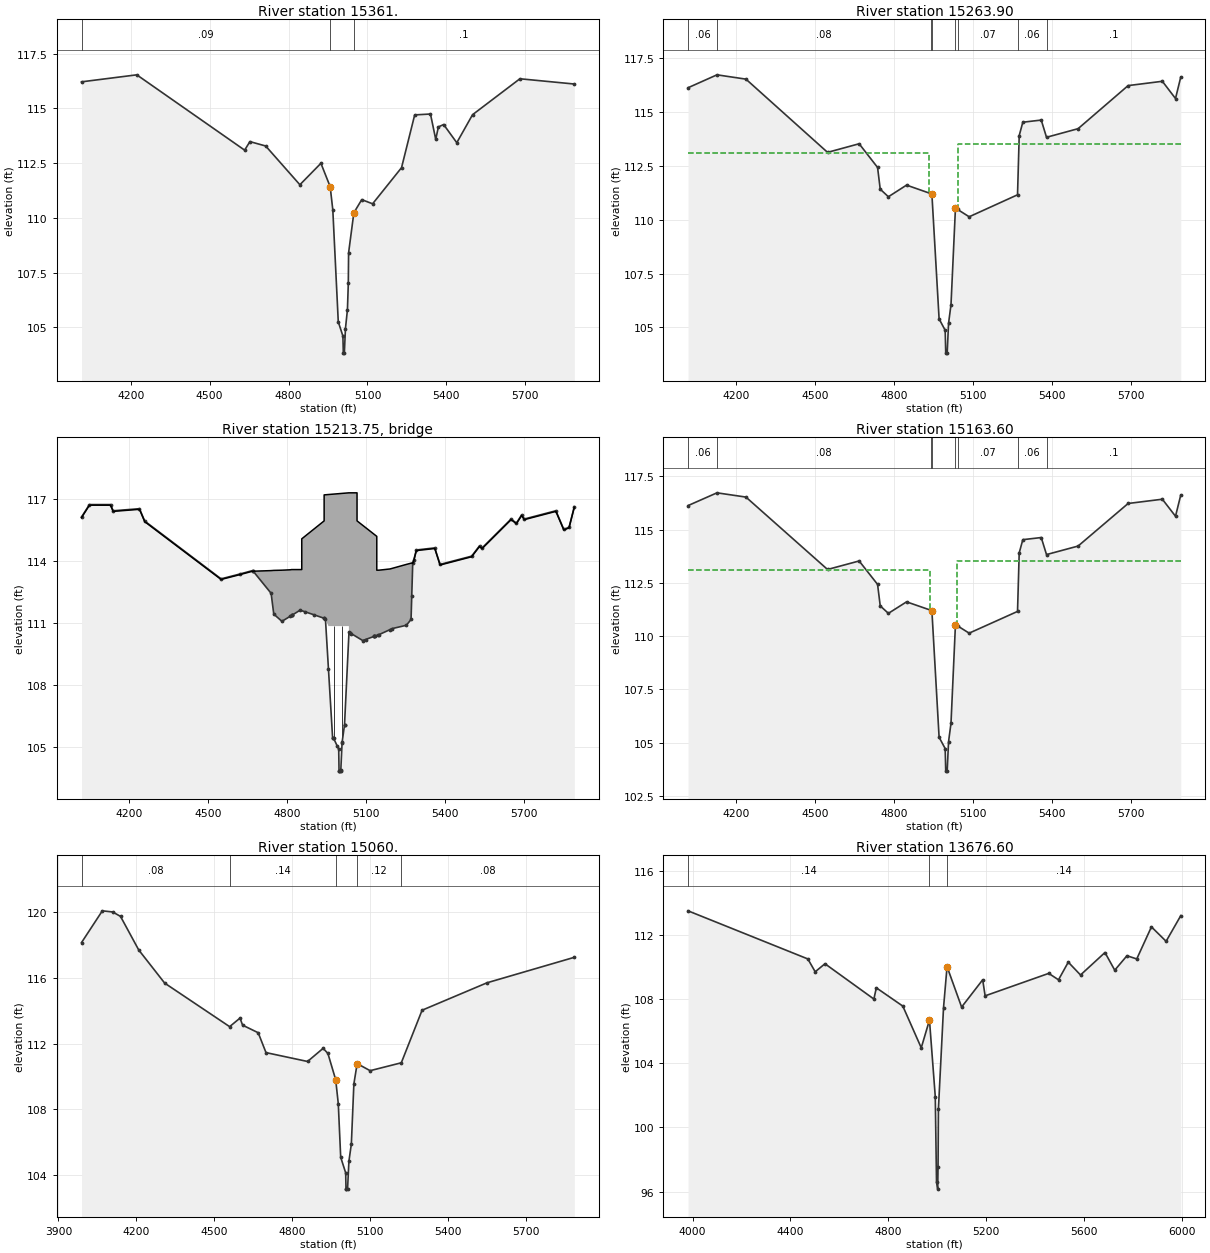
Type RM Length L Ch R = 1 ,15361.  ,85,97.1,101
BEGIN DESCRIPTION:
interpolated channel - LIDAR overbanks
LOUETTA - XS 4
END DESCRIPTION:
XS GIS Cut Line= 4
      3101488.37     13955526.81      3100676.34     13955083.39
      3100535.53     13955094.98      3099761.58     13955323.03
#Sta/Elev= 30
  4013.1  116.21  4223.1  116.53  4633.1  113.09  4653.1  113.48  4713.1  113.28
  4843.1  111.51  4923.1  112.49  4958.3  111.42  4968.3  110.36 4989.06  105.25
 5006.64   104.6 5008.24  103.82 5012.11  103.82 5016.35  104.94 5023.93  105.81
  5027.2     107  5028.3   108.4  5048.3  110.23  5078.3  110.83  5119.6  110.64
  5229.6  112.29  5279.6   114.7  5339.6  114.74  5359.6  113.58  5369.6  114.15
  5389.6  114.26  5439.6  113.43  5499.6  114.71  5679.6  116.35  5886.4  116.11
#Mann= 3 ,-1 , 0
  4013.1     .09       0  4958.3     .04       0  5048.3      .1       0
Bank Sta=4958.3,5048.3
XS Rating Curve= 0
Exp/Cntr=.5,.3

Type RM Length L Ch R = 1 ,15263.90,100.3,100.3,100.3
BEGIN DESCRIPTION:
Upstream Section of Bridge/Culvert/Weir Louetta
LOUETTA - XS 3
END DESCRIPTION:
XS GIS Cut Line= 4
      3101467.55      13955429.6      3100669.85     13955000.75
      3100494.23     13954988.57      3099740.76      13955225.8
#Sta/Elev= 30
  4018.6  116.13  4128.6  116.73  4238.6  116.53  4548.6  113.13  4668.6  113.53
  4738.6  112.43  4748.7  111.42  4779.7  111.07  4848.7  111.61 4939.81  111.22
  4944.9   111.2  4972.3   105.4  4995.4  104.87  4997.5  103.81    5003  103.81
  5008.2  105.19  5017.5  106.06  5034.4  110.54  5042.5  110.48  5086.5  110.14
  5270.2  111.16  5276.6  113.91  5290.3  114.53  5360.3  114.63  5380.3  113.83
  5500.3  114.23  5690.3  116.23  5820.3  116.43  5870.3  115.63  5890.3  116.63
#Mann= 8 ,-1 , 0
  4018.6     .06       0  4128.6     .08       0 4939.81    .045       0
  4944.9    .055       0  5034.4    .045       0  5042.5     .07       0
  5270.2     .06       0  5380.3      .1       0
#XS Ineff= 2 , 0
       0  4934.9   113.1  5044.4       0  113.53
Permanent Ineff=
       F       F
Bank Sta=4944.9,5034.4
XS Rating Curve= 0
Exp/Cntr=.5,.3

Type RM Length L Ch R = 3 ,15213.75,,,
BEGIN DESCRIPTION:
LOUETTA
Structure ID: K120-00-00-S4
END DESCRIPTION:
Bridge Culvert--1,0,-1,-1, 0
Deck Dist Width WeirC Skew NumUp NumDn MinLoCord MaxHiCord MaxSubmerge Is_Ogee
10,83,2.6,0, 48, 48, , , .95, 0, ,,,
  4018.6  4048.6  4128.6  4138.6  4238.6  4258.6  4548.6  4618.8    4668  4668.6
  4738.6  4748.7  4779.7  4811.8 4816.69    4855 4855.01    4940 4940.01    5034
 5034.01    5065 5065.01    5140 5140.01    5145  5147.6  5190.4  5198.9  5252.4
  5270.2  5272.9  5276.6  5280.3  5290.3  5360.3  5380.3  5500.3  5530.3  5540.3
  5650.3  5670.3  5690.3  5700.3  5820.3  5850.3  5870.3  5890.3
   116.1   116.7   116.7   116.4   116.5   115.9   113.1  113.33   113.5   113.5
  113.53  113.54  113.55  113.57  113.58  113.58  115.07  115.94   117.2   117.3
   117.3   117.3  115.94  115.19  113.55  113.55  113.55  113.61  113.64  113.83
  113.89   113.9  113.88     114   114.5   114.6   113.8   114.2   114.7   114.6
     116   115.8   116.2     116   116.4   115.5   115.6   116.6
   116.1   116.7   116.7   116.4   116.5   115.9   113.1  113.33   113.5   113.5
   112.4  111.39  111.04  111.29  111.33  110.84  110.84  110.84  110.84  110.84
     110     110     110     110     110     110  110.39  110.64  110.69  110.85
  111.13  112.29  113.88     114   114.5   114.6   113.8   114.2   114.7   114.6
     116   115.8   116.2     116   116.4   115.5   115.6   116.6
  4018.6  4048.6  4128.6  4138.6  4238.6  4258.6  4548.6  4618.8    4668  4668.6
  4738.6  4748.7  4779.7  4811.8 4816.69    4855 4855.01    4940 4940.01    5034
 5034.01    5065 5065.01    5140 5140.01    5145  5147.6  5190.4  5198.9  5252.4
  5270.2  5272.9  5276.6  5280.3  5290.3  5360.3  5380.3  5500.3  5530.3  5540.3
  5650.3  5670.3  5690.3  5700.3  5820.3  5850.3  5870.3  5890.3
   116.1   116.7   116.7   116.4   116.5   115.9   113.1  113.33   113.5   113.5
  113.53  113.54  113.55  113.57  113.58  113.58  115.07  115.94   117.2   117.3
   117.3   117.3  115.94  115.19  113.55  113.55  113.55  113.61  113.64  113.83
  113.89   113.9  113.88     114   114.5   114.6   113.8   114.2   114.7   114.6
     116   115.8   116.2     116   116.4   115.5   115.6   116.6
   116.1   116.7   116.7   116.4   116.5   115.9   113.1  113.33   113.5   113.5
   112.4  111.39  111.04  111.29  111.33  110.83  110.83  110.83  110.83  110.83
     110     110     110     110     110     110  110.39  110.64  110.69  110.85
  111.13  112.29  113.88     114   114.5   114.6   113.8   114.2   114.7   114.6
     116   115.8   116.2     116   116.4   115.5   115.6   116.6
Pier Skew, UpSta & Num, DnSta & Num=  ,4977.2, 2 ,4977.2, 2 , 0 , 0 , 0 ,,
     1.3     1.3
  104.32  112.71
     1.3     1.3
   105.2  113.59
Pier Skew, UpSta & Num, DnSta & Num=  ,5008.6, 2 ,5008.6, 2 , 0 , 0 , 0 ,,
     1.3     1.3
  104.09  112.68
     1.3     1.3
  104.97  113.56
BR Coef= 1 , 1 , 1 ,1.25, 0 ,,,.8,0,2,0,
WSPro=,,,, 1 ,,,, 0 ,,,, 0 ,,,,-1 ,-1 ,-1 , 0 , 0 , 0 , 0 , 0
BR U #Sta/Elev= 71
  4018.6  116.13  4048.6  116.73  4128.6  116.73  4138.6  116.43  4238.6  116.53
  4258.6  115.93  4548.6  113.13  4618.8  113.36    4668  113.53  4668.6  113.53
  4738.6  112.43  4748.7  111.42  4779.7  111.07  4811.8  111.32 4816.69  111.36
  4816.8  111.36 4816.91  111.36  4848.7  111.61  4866.1  111.54  4903.2  111.38
 4939.81  111.22  4939.9  111.22  4944.9   111.2  4956.4  108.77  4972.2  105.42
  4972.3   105.4  4975.7  105.41  4989.3  105.04  4995.4  104.87  4996.6  103.84
  4997.5  103.81    4999  103.81    5003  103.81  5003.4  103.87  5008.2  105.19
  5008.6  105.23  5017.4  106.05  5017.5  106.06  5034.4  110.54 5039.39   110.5
  5039.5   110.5  5042.5  110.48  5086.5  110.14  5097.2  110.19 5129.79  110.34
  5129.9  110.34 5130.01  110.34  5133.8  110.36    5145  110.41  5147.6  110.42
  5190.4  110.67  5198.9  110.72  5252.4  110.88  5270.2  111.16  5272.9  112.32
  5276.6  113.91  5280.3  114.03  5290.3  114.53  5360.3  114.63  5380.3  113.83
  5500.3  114.23  5530.3  114.73  5540.3  114.63  5650.3  116.03  5670.3  115.83
  5690.3  116.23  5700.3  116.03  5820.3  116.43  5850.3  115.53  5870.3  115.63
  5890.3  116.63
BR U #Mann= 10
  4018.6     .06  4128.6     .08 4939.81    .045  4944.9    .025  4975.7     .04
  5008.6    .025  5034.4    .045  5042.5     .07  5270.2     .06  5380.3      .1
BR U Banks=4944.9,5034.4
BR D #Sta/Elev= 71
  4018.6  116.13  4048.6  116.73  4128.6  116.73  4138.6  116.43  4238.6  116.53
  4258.6  115.93  4548.6  113.13  4618.8  113.36    4668  113.53  4668.6  113.53
  4738.6  112.43  4748.7  111.42  4779.7  111.07  4811.8  111.32 4816.69  111.36
  4816.8  111.36 4816.91  111.36  4848.7  111.61  4866.1  111.54  4903.2  111.38
 4939.81  111.22  4939.9  111.22  4944.9   111.2  4956.4  108.62  4972.2  105.27
  4972.3  105.25  4975.7  105.26  4989.3  104.89  4995.4  104.72  4996.6  103.69
  4997.5  103.66    4999  103.66    5003  103.66  5003.4  103.72  5008.2  105.04
  5008.6  105.08  5017.4   105.9  5017.5  105.91  5034.4  110.54 5039.39   110.5
  5039.5   110.5  5042.5  110.48  5086.5  110.14  5097.2  110.19 5129.79  110.34
  5129.9  110.34 5130.01  110.34  5133.8  110.36    5145  110.41  5147.6  110.42
  5190.4  110.67  5198.9  110.72  5252.4  110.88  5270.2  111.16  5272.9  112.32
  5276.6  113.91  5280.3  114.03  5290.3  114.53  5360.3  114.63  5380.3  113.83
  5500.3  114.23  5530.3  114.73  5540.3  114.63  5650.3  116.03  5670.3  115.83
  5690.3  116.23  5700.3  116.03  5820.3  116.43  5850.3  115.53  5870.3  115.63
  5890.3  116.63
BR D #Mann= 10
  4018.6     .06  4128.6     .08 4939.81    .045  4944.9    .025  4975.7     .04
  5008.6    .025  5034.4    .045  5042.5     .07  5270.2     .06  5380.3      .1
BR D Banks=4944.9,5034.4
BC Design=,, 0 ,, 0 ,,,,,,
BC HTab HWMax=116.73

Type RM Length L Ch R = 1 ,15163.60,118,103.6,88
BEGIN DESCRIPTION:
Downstream Section of Bridge/Culvert/Weir  Louetta
LOUETTA - XS 2
END DESCRIPTION:
XS GIS Cut Line= 4
      3101463.94      13955333.5      3100662.45     13954902.63
      3100478.76     13954889.89      3099721.68      13955128.3
#Sta/Elev= 30
  4018.6  116.13  4128.6  116.73  4238.6  116.53  4548.6  113.13  4668.6  113.53
  4738.6  112.43  4748.7  111.42  4779.7  111.07  4848.7  111.61 4939.81  111.22
  4944.9   111.2  4972.3  105.25  4995.4  104.72  4997.5  103.66    5003  103.66
  5008.2  105.04  5017.5  105.91  5034.4  110.54  5042.5  110.48  5086.5  110.14
  5270.2  111.16  5276.6  113.91  5290.3  114.53  5360.3  114.63  5380.3  113.83
  5500.3  114.23  5690.3  116.23  5820.3  116.43  5870.3  115.63  5890.3  116.63
#Mann= 8 ,-1 , 0
  4018.6     .06       0  4128.6     .08       0 4939.81    .045       0
  4944.9     .04       0  5034.4    .045       0  5042.5     .07       0
  5270.2     .06       0  5380.3      .1       0
#XS Ineff= 2 , 0
       0 4938.23   113.1 5041.07       0  113.53
Permanent Ineff=
       F       F
Bank Sta=4944.9,5034.4
XS Rating Curve= 0
Exp/Cntr=.5,.3

Type RM Length L Ch R = 1 ,15060.  ,1409,1383.4,1326
BEGIN DESCRIPTION:
interpolated channel - LIDAR overbanks
LOUETTA - XS 1
END DESCRIPTION:
XS GIS Cut Line= 4
      3101445.44     13955241.07       3100616.7     13954780.22
      3100507.29     13954806.97      3099703.18     13955035.83
#Sta/Elev= 30
    3989  118.15    4069  120.08    4109  120.01    4139  119.74    4209   117.7
    4309  115.68    4559  113.03    4599  113.55    4609  113.12    4669  112.66
    4699  111.45    4859  110.91    4919  111.71  4937.3   111.4  4967.3   109.8
  4977.3  108.34 4986.59  105.08 5005.79  104.13 5006.96  103.17 5007.84  103.14
 5012.96  103.14 5018.24  104.84 5027.58  105.88  5037.3  109.54  5049.9  110.78
  5099.9  110.35  5219.9  110.83  5299.9  114.03  5549.9   115.7  5885.9  117.25
#Mann= 5 ,-1 , 0
    3989     .08       0    4559     .14       0  4967.3     .04       0
  5049.9     .12       0  5219.9     .08       0
Bank Sta=4967.3,5049.9
XS Rating Curve= 0
Exp/Cntr=.3,.1

Type RM Length L Ch R = 1 ,13676.60,293,346.6,389
BEGIN DESCRIPTION:
Cross Section K120-00-00-X7
END DESCRIPTION:
XS GIS Cut Line= 4
      3101398.79      13953357.5      3100460.06     13953489.88
      3100436.72     13953634.88      3099775.48      13954274.5
#Sta/Elev= 30
  3981.4   113.5  4471.4   110.5  4501.4   109.7  4541.4   110.2  4741.4     108
  4751.4   108.7  4859.7  107.56  4935.1  104.96  4968.7  106.69  4992.4  101.92
  4997.5    96.6  5002.4   96.15  5003.8   97.54  5005.3  101.15  5026.1  107.45
  5040.6  110.02  5100.1   107.5  5186.3   109.2  5196.3   108.2  5456.3   109.6
  5496.3   109.2  5536.3   110.3  5586.3   109.5  5686.3   110.9  5726.3   109.8
  5776.3   110.7  5816.3   110.5  5876.3   112.5  5936.3   111.6  5996.3   113.2
#Mann= 3 ,-1 , 0
  3981.4     .14       0  4968.7     .08       0  5040.6     .14       0
Bank Sta=4968.7,5040.6
XS Rating Curve= 0
Exp/Cntr=.3,.1