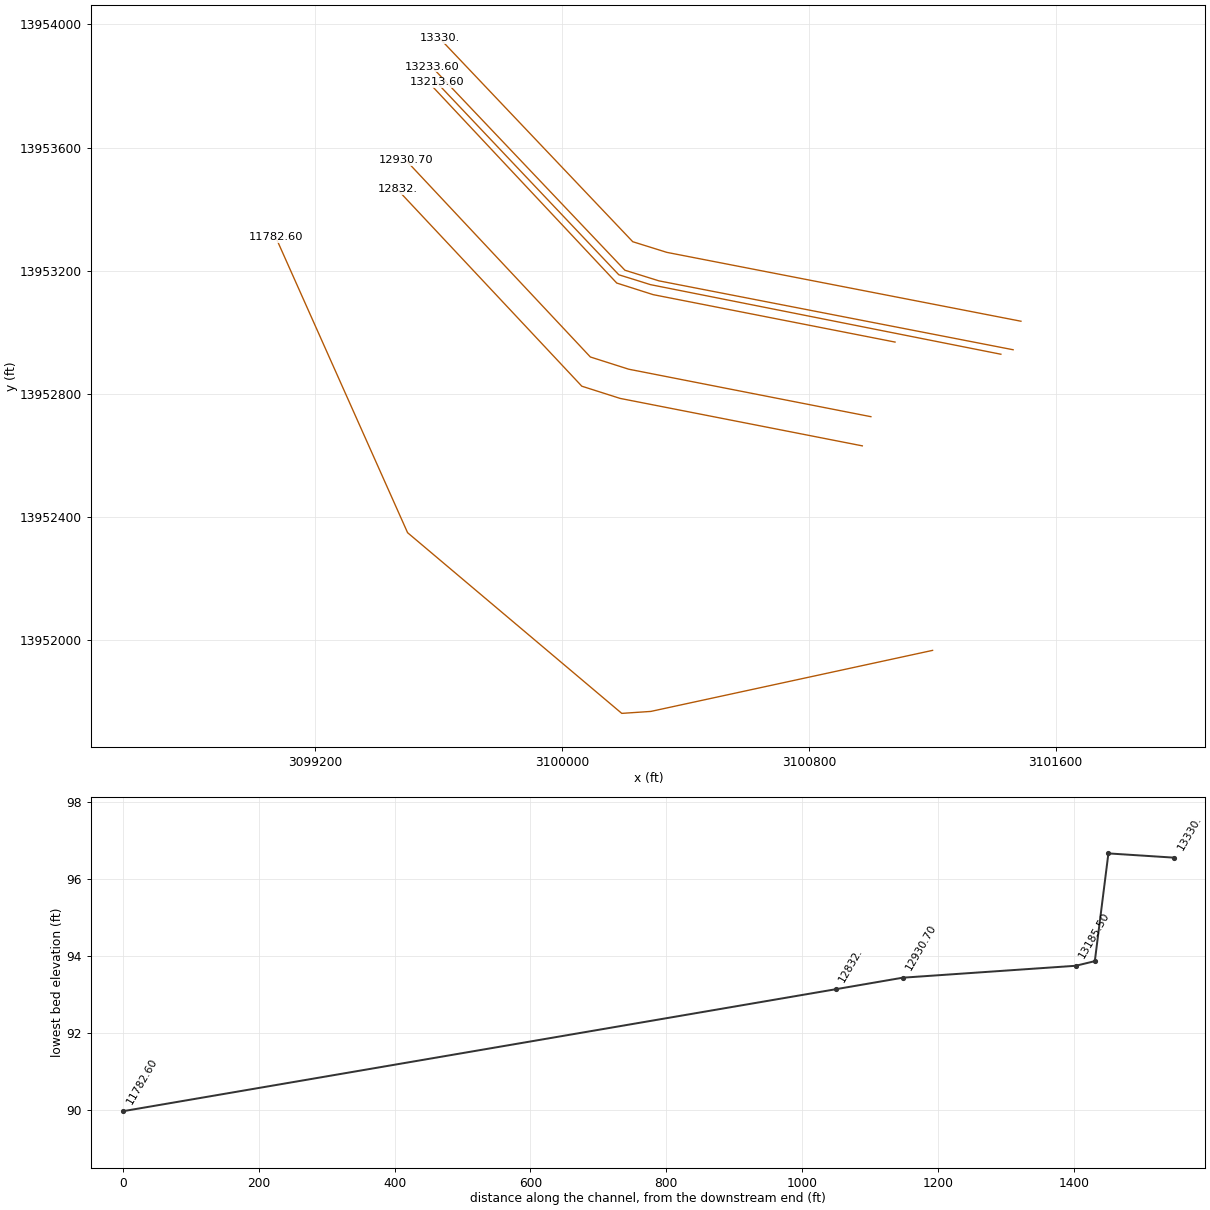
HEC-RAS study K120-00-00.prj: K120-00-00

--- K120-00-00.g01 (geometry) --- (continued)

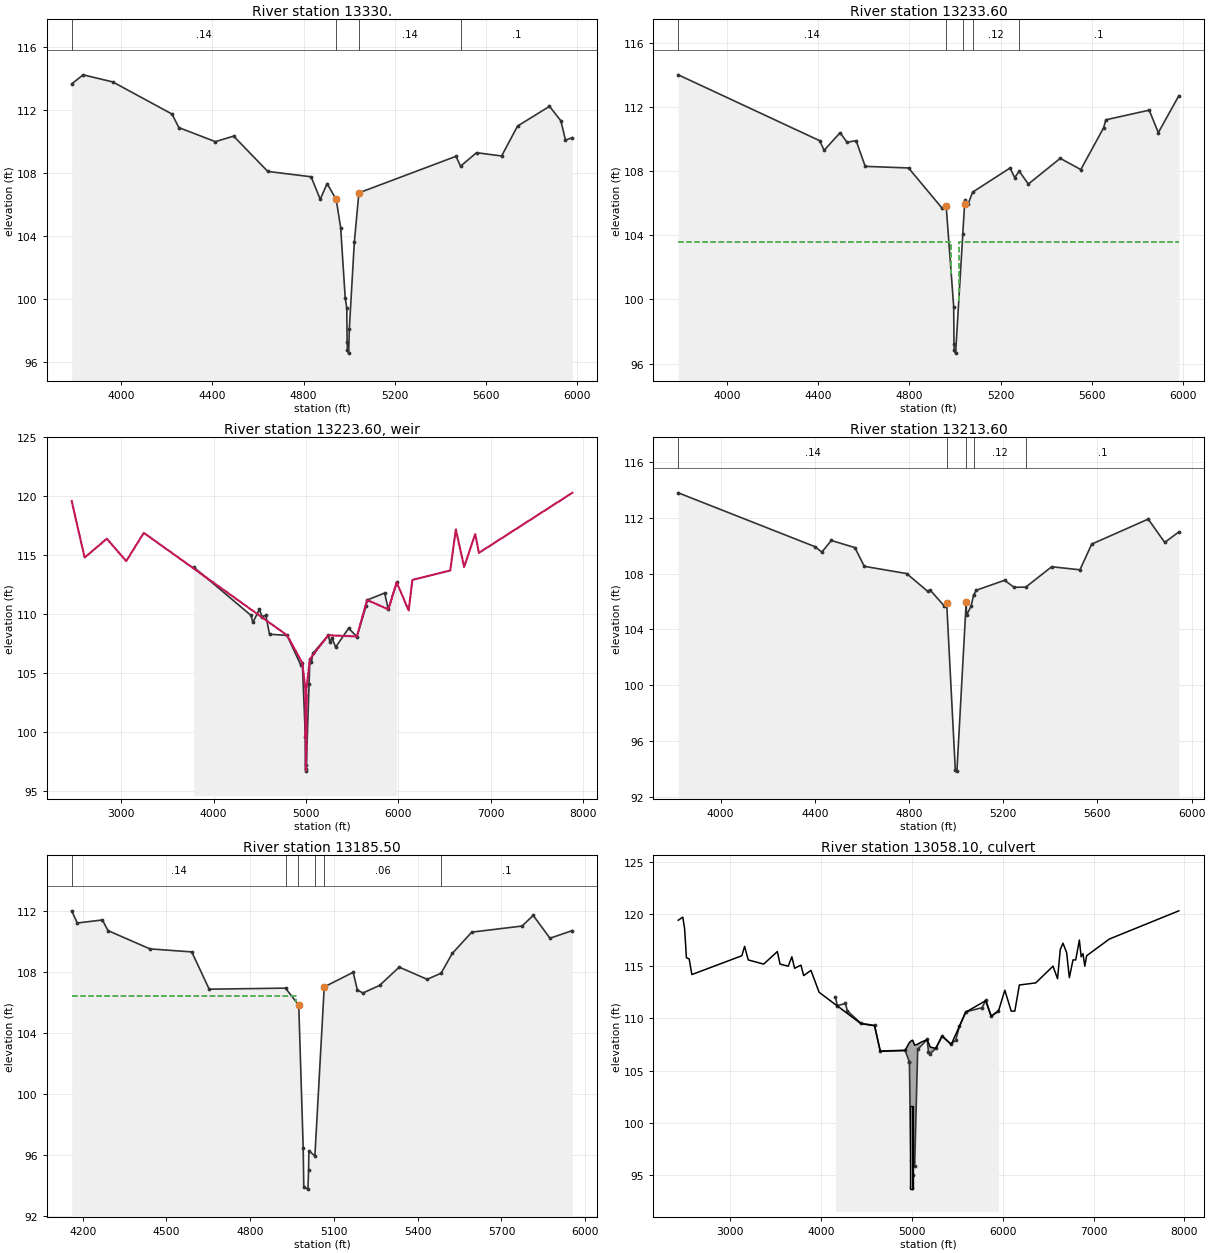
Type RM Length L Ch R = 1 ,13330.  ,97,96.4,95
BEGIN DESCRIPTION:
interpolated channel - LIDAR overbanks
SHEET PILING DROP STRUCTURE 45' US OF LEXINGTON RD - XS 4
END DESCRIPTION:
XS GIS Cut Line= 4
      3101487.49     13953036.38       3100339.5      13953259.9
      3100228.92     13953294.45      3099602.78     13953954.76
#Sta/Elev= 30
  3782.7  113.63  3832.7  114.21  3962.7  113.76  4222.7  111.72  4252.7  110.86
  4412.7  109.97  4492.7  110.32  4642.7  108.08  4832.7  107.74  4872.7  106.31
  4902.7  107.31  4942.7   106.3  4962.2  104.52  4982.2  100.06 4989.17    99.4
 4990.51   97.28 4991.85   96.77 4997.32   96.55 5000.35   98.11  5022.2  103.59
  5042.2  106.72  5468.1  109.04  5488.1  108.41  5558.1  109.27  5668.1  109.06
  5738.1  110.96  5878.1  112.21  5928.1  111.29  5948.1  110.07  5978.1  110.22
#Mann= 4 ,-1 , 0
  3782.7     .14       0  4942.7    .045       0  5042.2     .14       0
  5488.1      .1       0
Bank Sta=4942.7,5042.2
XS Rating Curve= 0
Exp/Cntr=.7,.5

Type RM Length L Ch R = 1 ,13233.60,20,20,20
BEGIN DESCRIPTION:
Upstream Section of Bridge/Culvert/Weir
SHEET PILING DROP STRUCTURE 45' US OF LEXINGTON RD - XS 3
END DESCRIPTION:
XS GIS Cut Line= 4
      3101462.04      13952943.8      3100314.06     13953167.38
      3100203.47     13953201.94      3099577.33      13953862.2
#Sta/Elev= 30
  3785.9  113.99  4405.9  109.89  4425.9  109.29  4495.9  110.39  4525.9  109.79
  4565.9  109.89  4605.9  108.29  4795.9  108.19    4944  105.67  4960.9  105.82
  4993.9   99.56  4995.2   97.21  4996.6   96.83  5002.3   96.66  5033.8  104.07
  5042.6  106.17  5042.7  105.96  5057.4  105.95  5076.6  106.68  5241.3  108.19
  5261.3  107.59  5281.3  107.99  5321.3  107.19  5461.3  108.79  5551.3  108.09
  5651.3  110.69  5661.3  111.19  5851.3  111.79  5891.3  110.39  5981.3  112.69
#Mann= 5 ,-1 , 0
  3785.9     .14       0  4960.9     .02       0  5033.8    .045       0
  5076.6     .12       0  5281.3      .1       0
#XS Ineff= 2 , 0
       0    4984   103.6    5016       0   103.6
Permanent Ineff=
       F       F
Bank Sta=4960.9,5042.7
XS Rating Curve= 0
Exp/Cntr=.7,.5

Type RM Length L Ch R = 5 ,13223.60,,,
BEGIN DESCRIPTION:
SHEET PILING DROP STRUCTURE 45' US OF LEXINGTON RD.
***SEE NOTES BELOW***
***U/S N VALUE IS 0.06.  D/S N IS O.O3***
Structure ID: K120-00-00-S3b
END DESCRIPTION:
IW Pilot Flow=0
#Inline Weir SE= 30
  2465.9   119.6  2605.9   114.8  2845.9   116.4  3055.9   114.5  3245.9   116.9
  4795.9   108.2  4960.9  105.84  4993.8  103.63    4994   99.57  4996.7   99.61
  4996.9    96.8  5002.3   96.68  5003.2   96.76  5003.5   99.64    5006   99.63
  5006.1  103.66  5042.6  106.19  5241.3   108.2  5551.3   108.1  5661.3   111.2
  5891.3   110.4  5981.3   112.7  6111.3   110.3  6151.3   112.9  6561.3   113.7
  6621.3   117.2  6711.3     114  6831.3   116.8  6871.3   115.2  7881.4   120.3
IW Dist,WD,Coef,Skew,MaxSub,Min_El,Is_Ogee,SpillHt,DesHd
10,1,3,0,.95,, 0 ,,,0,0,

Type RM Length L Ch R = 1 ,13213.60,28,28.1,28.1
BEGIN DESCRIPTION:
Cross Section FIELD_DS
SHEET PILING DROP STRUCTURE 45' US OF LEXINGTON RD - XS 2
LEXINGTON RD. - XS 4
***SEE NOTES BELOW***
***U/S N VALUE IS 0.06.  D/S N IS O.O3***
Located At: SHEET PILING DROP STRUCTURE 45' US OF LEXINGTON RD.
END DESCRIPTION:
XS GIS Cut Line= 5
      3101422.43      13952929.2      3100286.29     13953155.13
      3100232.97      13953171.9      3100183.73     13953187.13
      3099592.88      13953811.9
#Sta/Elev= 28
    3820  113.78    4400  109.93    4430  109.54    4470  110.37    4570  109.86
    4610  108.52    4790     108    4880  106.72    4890  106.81    4950  105.68
  4959.9  105.86    4960  105.86  4996.6   93.93  5003.4   93.86  5042.8  105.97
  5044.3  105.01  5064.3  105.71  5074.3  106.47  5085.8  106.81  5205.8  107.52
  5245.8  107.02  5295.8  107.03  5405.8  108.49  5525.8  108.27  5575.8  110.11
  5815.8   111.9  5885.8  110.23  5945.8  110.98
#Mann= 5 ,-1 , 0
    3820     .14       0  4959.9     .02       0  5042.8    .045       0
  5074.3     .12       0  5295.8      .1       0
Bank Sta=4959.9,5042.8
XS Rating Curve= 0
Exp/Cntr=.7,.5

Type RM Length L Ch R = 1 ,13185.50,254.8,254.8,254.8
BEGIN DESCRIPTION:
Upstream Section of Bridge/Culvert/Weir
LEXINGTON RD. - XS 3
END DESCRIPTION:
XS GIS Cut Line= 4
       3101079.3      13952968.7      3100295.09     13953122.64
      3100177.01     13953160.32      3099582.35      13953795.4
#Sta/Elev= 30
  4160.6  112.03  4180.6  111.23  4270.6  111.43  4290.6  110.73  4440.6  109.53
  4590.6  109.33  4653.1  106.88  4926.5  106.95 4972.79  105.85  4973.9  105.83
  4989.8   96.46  4991.9   93.87  5006.7   93.74  5009.1   94.97  5010.2   96.26
  5031.7   95.92  5065.2  107.03  5168.9  107.99  5183.7  106.83  5203.7  106.63
  5263.7  107.13  5333.7  108.33  5433.7  107.53  5483.7  107.93  5523.7  109.23
  5593.7  110.63  5773.7  111.03  5813.7  111.73  5873.7  110.23  5953.7  110.73
#Mann= 6 ,-1 , 0
  4160.6     .14       0  4926.5    .045       0 4972.79     .02       0
  5031.7    .045       0  5065.2     .06       0  5483.7      .1       0
#XS Ineff= 2 , 0
       0  4963.9  106.43  5075.2       0   107.1
Permanent Ineff=
       F       F
Bank Sta=4973.9,5065.2
XS Rating Curve= 0
Exp/Cntr=.5,.3

Type RM Length L Ch R = 2 ,13058.10,,,
BEGIN DESCRIPTION:
LEXINGTON RD.  field surveyed negative culvert slope
 ***SEE NOTES BELOW***
***D/S N VALUE SHOULD BE 0.04***
***U/S N VALUE SHOULD BE 0.03***
***U/S XS SHOULD MATCH D/S XS OF WEIR***
***MAKE CHANGES IN RAS***
Structure ID: K120-00-00-S3a
END DESCRIPTION:
Bridge Culvert--1,0,-1,-1, 0
Deck Dist Width WeirC Skew NumUp NumDn MinLoCord MaxHiCord MaxSubmerge Is_Ogee
10,236,3,0, 60, 60, , , .95, 0, ,,,
  2430.6  2480.6  2500.6  2520.6  2550.6  2580.6  3130.6  3160.6  3200.6  3370.6
  3520.6  3550.6  3640.6  3680.6  3710.6  3780.6  3810.6  3890.6  3980.6  4440.6
  4590.6  4653.1  4926.5  4973.9  4989.8  4991.9  5006.7  5010.2  5031.7  5065.2
  5101.6  5168.9  5203.7  5263.7  5333.7  5433.7  5593.7  5813.7  5873.7  5953.7
  6023.7  6093.7  6133.7  6183.7  6363.7  6553.7  6603.7  6633.7  6663.7  6703.7
  6733.7  6773.7  6803.7  6843.7  6863.7  6883.7  6903.7  6923.7  7173.7  7938.3
   119.4   119.7   118.6   115.8   115.7   114.2     116   116.9   115.6   115.2
   116.4   115.2     115   115.9   114.8   115.1   114.1   114.6   112.5   109.5
   109.3  106.85  106.93   107.7  107.83  107.84  107.91  107.91  107.44  107.54
  107.72  107.97  107.26  107.13   108.3   107.5   110.6   111.7   110.2   110.7
   112.7   110.7   110.7   113.2   113.4     115   113.8   116.6   117.2   116.3
   113.9   115.6   115.6   117.5   115.9   116.2     115     116   117.6   120.3
   119.4   119.7   118.6   115.8   115.7   114.2     116   116.9   115.6   115.2
   116.4   115.2     115   115.9   114.8   115.1   114.1   114.6   112.5   109.5
   109.3  106.85  106.92   105.8   96.43   93.84   93.71   96.23   95.89     107
  107.58  107.96   106.6  107.13   108.3   107.5   110.6   111.7   110.2   110.7
   112.7   110.7   110.7   113.2   113.4     115   113.8   116.6   117.2   116.3
   113.9   115.6   115.6   117.5   115.9   116.2     115     116   117.6   120.3
  2430.6  2480.6  2500.6  2520.6  2550.6  2580.6  3130.6  3160.6  3200.6  3370.6
  3520.6  3550.6  3640.6  3680.6  3710.6  3780.6  3810.6  3890.6  3980.6  4440.6
  4590.6  4653.1  4926.5  4973.9  4989.8  4991.9  4999.1  5006.7  5010.2  5031.7
  5065.2  5168.9  5203.7  5263.7  5333.7  5483.7  5593.7  5813.7  5873.7  5953.7
  6023.7  6093.7  6133.7  6183.7  6363.7  6553.7  6603.7  6633.7  6663.7  6703.7
  6733.7  6773.7  6803.7  6843.7  6863.7  6883.7  6903.7  6923.7  7173.7  7938.3
  119.12  119.42  118.32  115.52  115.42  113.92  115.72  116.62  115.32  114.92
  116.12  114.92  114.72  115.62  114.52  114.82  113.82  114.32  112.22  109.22
  109.02  106.85  106.93   107.7  107.83  107.84   107.9  107.91  107.91  107.44
  107.54  107.97  107.26  106.82  108.02  107.62  110.32  111.42  109.92  110.42
  112.42  110.42  110.42  112.92  113.12  114.72  113.52  116.32  116.92  116.02
  113.62  115.32  115.32  117.22  115.62  115.92  114.72  115.72  117.32  120.02
  119.12  119.42  118.32  115.52  115.42  113.92  115.72  116.62  115.32  114.92
  116.12  114.92  114.72  115.62  114.52  114.82  113.82  114.32  112.22  109.22
  109.02  106.57  106.64  105.52   96.15   93.56   93.44   93.43   95.95   95.61
  106.72  107.68  106.32  106.82  108.02  107.62  110.32  111.42  109.92  110.42
  112.42  110.42  110.42  112.92  113.12  114.72  113.52  116.32  116.92  116.02
  113.62  115.32  115.32  117.22  115.62  115.92  114.72  115.72  117.32  120.02
BR Coef= 1 , 0 , 0 ,1.25, 0 ,,,.8,-1,2,0,
WSPro=,,,, 1 ,,,, 0 ,,,, 0 ,,,,-1 ,-1 ,-1 , 0 , 0 , 0 , 0 , 0
Culvert=2,8,14,236,.015,.4,1,8,1,93.66,4992.1,94.67,4992.1,Culvert #1  , 0 ,10
Culvert Bottom n=.015
Culvert=2,8,14,236,.015,.4,1,8,1,93.66,5007.1,94.67,5007.1,Culvert #2  , 0 ,10
Culvert Bottom n=.015
BC Design=,, 0 ,, 0 ,,,,,,
BC HTab HWMax=112.03

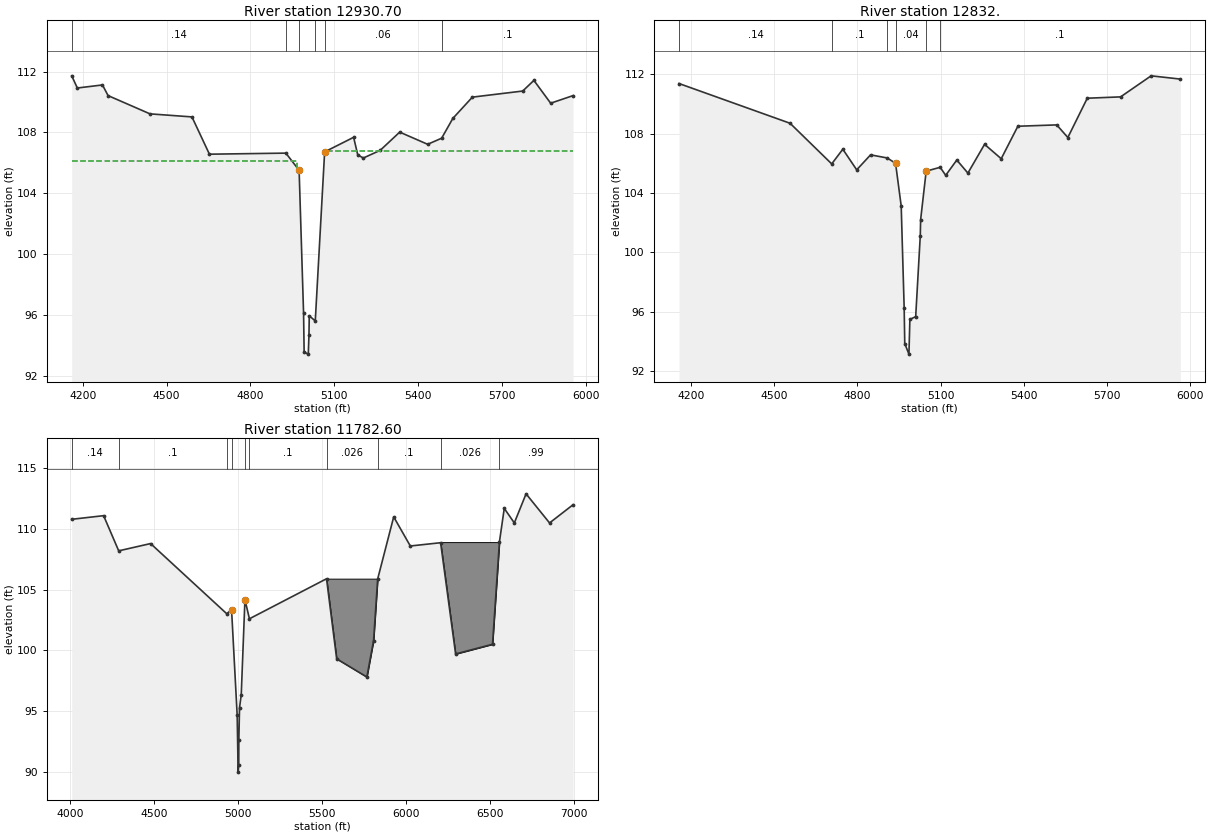
Type RM Length L Ch R = 1 ,12930.70,93,98.7,102
BEGIN DESCRIPTION:
Downstream Section of Bridge/Culvert/Weir
LEXINGTON RD. - XS 2
END DESCRIPTION:
XS GIS Cut Line= 4
      3101000.95      13952726.5      3100215.62     13952880.66
      3100091.48     13952920.27      3099493.26      13953559.1
#Sta/Elev= 30
  4160.6  111.72  4180.6  110.92  4270.6  111.12  4290.6  110.42  4440.6  109.22
  4590.6  109.02  4653.1  106.57  4926.5  106.64 4972.79  105.54  4973.9  105.52
  4989.8   96.15  4991.9   93.56  5006.7   93.43  5009.1   94.66  5010.2   95.95
  5031.7   95.61  5065.2  106.72  5168.9  107.68  5183.7  106.52  5203.7  106.32
  5263.7  106.82  5333.7  108.02  5433.7  107.22  5483.7  107.62  5523.7  108.92
  5593.7  110.32  5773.7  110.72  5813.7  111.42  5873.7  109.92  5953.7  110.42
#Mann= 6 ,-1 , 0
  4160.6     .14       0  4926.5    .045       0 4972.79     .04       0
  5031.7    .045       0  5065.2     .06       0  5483.7      .1       0
#XS Ineff= 2 , 0
       0 4967.23  106.12 5071.87       0  106.79
Permanent Ineff=
       F       F
Bank Sta=4973.9,5065.2
XS Rating Curve= 0
Exp/Cntr=.5,.3

Type RM Length L Ch R = 1 ,12832.  ,991,1049.4,1093
BEGIN DESCRIPTION:
interpolated channel - LIDAR overbanks
LEXINGTON RD. - XS 1
END DESCRIPTION:
XS GIS Cut Line= 4
       3100973.2     13952631.75      3100187.86     13952785.83
      3100063.73     13952825.44      3099465.51     13953464.34
#Sta/Elev= 30
  4157.9  111.38  4557.9   108.7  4707.9  105.96  4747.9  106.95  4797.9  105.56
  4847.9  106.57  4907.9  106.36  4937.9     106  4958.2  103.12 4968.89   96.25
 4971.02   93.84 4986.07   93.13 4989.48   95.47 5010.41   95.66 5026.95  101.12
  5028.2   102.2  5048.2  105.47  5098.5  105.73  5118.5  105.19  5158.5  106.22
  5198.5  105.34  5258.5  107.28  5318.5  106.31  5378.5   108.5  5518.5  108.59
  5558.5  107.74  5628.5  110.39  5748.5  110.48  5858.5   111.9  5963.8  111.68
#Mann= 6 ,-1 , 0
  4157.9     .14       0  4707.9      .1       0  4907.9    .045       0
  4937.9     .04       0  5048.2    .045       0  5098.5      .1       0
Bank Sta=4937.9,5048.2
XS Rating Curve= 0
Exp/Cntr=.3,.1

Type RM Length L Ch R = 1 ,11782.60,134,113.6,98
BEGIN DESCRIPTION:
Cross Section K120-00-00-X06
 Detention ponds on right VRR
END DESCRIPTION:
XS GIS Cut Line= 5
      3101200.99      13951967.8      3100287.57     13951769.64
      3100193.23     13951763.29      3099498.83     13952349.86
      3099071.43      13953308.9
#Sta/Elev= 30
  4007.4   110.8  4197.4   111.1  4287.4   108.2  4477.4   108.8  4931.1  103.02
  4960.2  103.34  4993.5   94.67  4999.4   89.96    5003   90.54  5003.5   92.57
  5007.6   95.26  5017.8   96.34  5039.8  104.18  5066.6   102.6  5526.2   105.9
  5586.6    99.3  5766.6    97.8  5806.6   100.8  5831.2  105.89  5926.6     111
  6025.6   108.6  6206.2  108.87  6295.6    99.7  6515.6   100.5    6557  108.95
  6585.6   111.7  6645.6   110.5  6715.6   112.9  6855.6   110.5  6995.6     112
#Mann= 10 ,-1 , 0
  4007.4     .14       0  4287.4      .1       0  4931.1    .045       0
  4960.2     .04       0  5039.8    .045       0  5066.6      .1       0
  5526.2    .026       0  5831.2      .1       0  6206.2    .026       0
    6557     .99       0
#Block Obstruct= 2 ,-1
    5527    5840  105.91    6206    6560  108.92
Bank Sta=4960.2,5039.8
XS Rating Curve= 0
Exp/Cntr=.3,.1