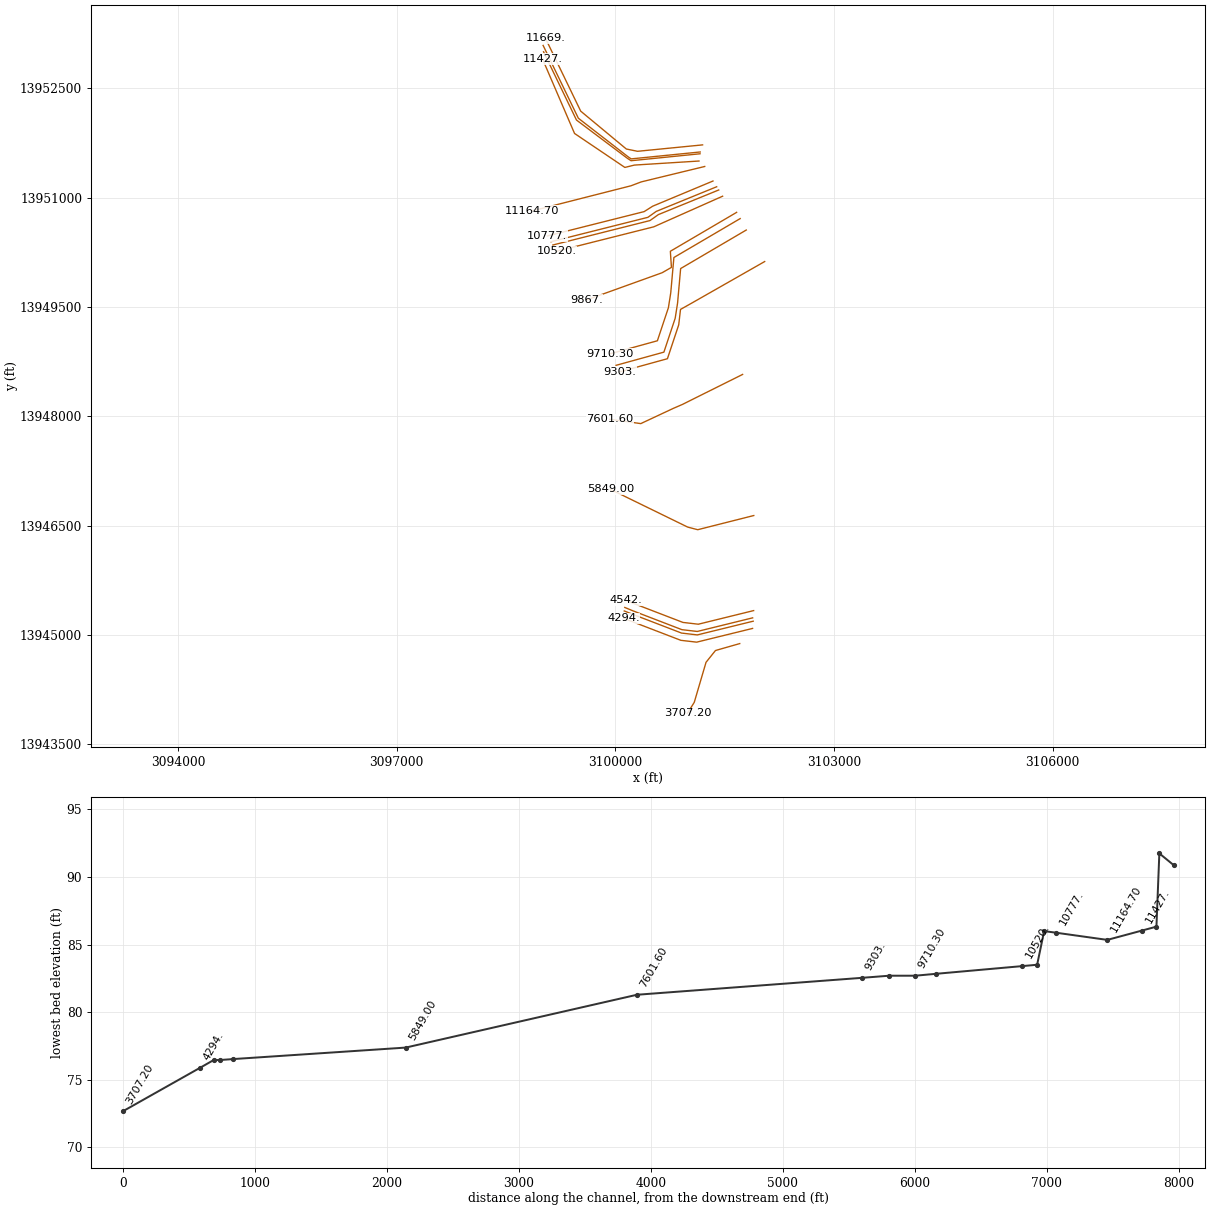
HEC-RAS study K120-00-00.prj: K120-00-00

--- K120-00-00.g01 (geometry) --- (continued)

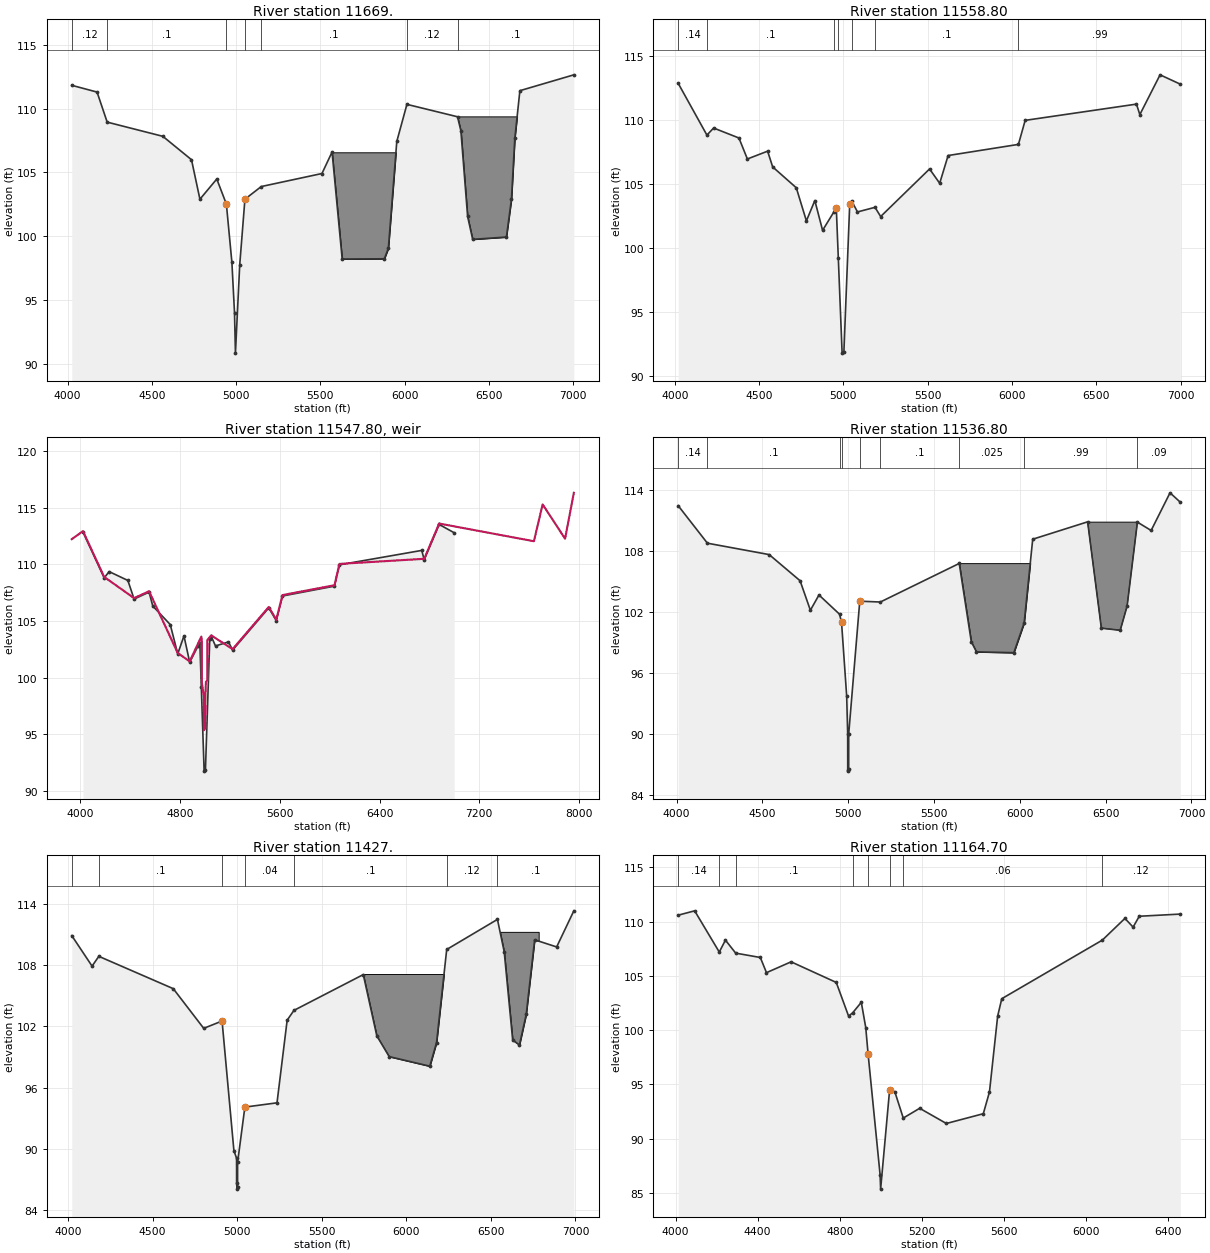
Type RM Length L Ch R = 1 ,11669.  ,117,110.2,95.5
BEGIN DESCRIPTION:
interpolated channel - LIDAR overbanks
WEIR +/- 1600' US CYPRESSWOOD DR. - XS 4
END DESCRIPTION:
XS GIS Cut Line= 5
      3101197.52     13951726.07      3100304.95     13951638.07
      3100151.31     13951669.32      3099524.98     13952189.11
      3099041.51     13953188.28
#Sta/Elev= 30
  4025.3  111.82  4175.3  111.29  4235.3  108.94  4565.3  107.83  4735.3     106
  4785.3  102.91  4885.3  104.49  4942.2  102.53 4974.91   97.97 4990.41   94.04
 4995.95   90.87 5021.28   97.76  5052.2  102.91    5149   103.9    5509  104.92
    5569   106.6    5629   98.23    5879   98.25  5902.9   99.07  5952.9  107.43
  6012.9  110.33  6312.9  109.36  6332.9  108.27  6372.9  101.56  6402.9   99.77
  6602.9   99.95  6632.9  102.91  6652.9  107.68  6682.9   111.4  7002.9  112.64
#Mann= 7 ,-1 , 0
  4025.3     .12       0  4235.3      .1       0  4942.2     .04       0
  5052.2    .045       0    5149      .1       0  6012.9     .12       0
  6312.9      .1       0
#Block Obstruct= 2 ,-1
 5568.41 5960.51  106.58 6310.84 6715.79  109.39
Bank Sta=4942.2,5052.2
XS Rating Curve= 0
Exp/Cntr=.7,.5

Type RM Length L Ch R = 1 ,11558.80,22,22,22
BEGIN DESCRIPTION:
Upstream Section of Bridge/Culvert/Weir
WEIR +/- 1600' US CYPRESSWOOD DR. - XS 3
Detention ponds not shown  VRR
END DESCRIPTION:
XS GIS Cut Line= 5
      3101165.13      13951628.9      3100217.42     13951533.98
      3100177.61     13951560.74       3099492.6     13952091.96
      3099009.12      13953091.1
#Sta/Elev= 30
  4020.8  112.84  4190.8   108.8  4230.8  109.35  4380.8  108.57  4430.8  106.93
  4550.8  107.54  4580.8  106.31  4720.8  104.68  4780.8  102.09  4830.8  103.68
  4876.8  101.35  4943.8  102.79  4958.1  103.09    4970    99.2  4992.6   91.75
  5003.1   91.84  5037.7  103.39  5049.9  103.63  5083.8  102.79  5187.6  103.15
  5221.2  102.43  5511.2  106.15  5571.2  105.03  5621.2   107.2  6038.1  108.07
  6078.1  109.95  6738.1  111.22  6758.1   110.4  6878.1  113.51  6998.1  112.78
#Mann= 7 ,-1 , 0
  4020.8     .14       0  4190.8      .1       0  4943.8    .045       0
    4970     .02       0  5049.9    .045       0  5187.6      .1       0
  6038.1     .99       0
#XS Ineff= 2 , 0
       0  4948.1  101.43  5047.7       0  102.51
Permanent Ineff=
       F       F
Bank Sta=4958.1,5037.7
XS Rating Curve= 0
Exp/Cntr=.7,.5

Type RM Length L Ch R = 5 ,11547.80,,,
BEGIN DESCRIPTION:
WEIR +/- 1600' US CYPRESSWOOD DR.
Structure ID: K120-00-00-S06
END DESCRIPTION:
IW Pilot Flow=0
#Inline Weir SE= 30
  3930.8  112.21  4020.8  112.92  4190.8  108.88  4430.8  107.01  4550.8  107.62
  4780.8  102.17  4876.8  101.43    4970  103.62  4974.1   103.2  4974.2   99.56
  4990.3   98.35  4990.6   95.35  5002.7   95.55  5002.9   98.51  5006.8   99.62
    5019   99.77  5019.1  103.33  5049.8  103.72  5221.2  102.51  5511.2  106.23
  5571.2  105.11  5621.2  107.28  6038.1  108.15  6078.1  110.03  6758.1  110.48
  6878.1  113.59  7638.1  112.03  7708.1  115.28  7888.1  112.25  7958.4   116.3
IW Dist,WD,Coef,Skew,MaxSub,Min_El,Is_Ogee,SpillHt,DesHd
10,1,3,0,.95,, 0 ,,,0,0,

Type RM Length L Ch R = 1 ,11536.80,71,109.8,139.9
BEGIN DESCRIPTION:
Cross Section FIELD_DS WEIR
Located At: WEIR +/- 1600' US CYPRESSWOOD DR. - XS 2
END DESCRIPTION:
XS GIS Cut Line= 5
      3101162.55       13951604.      3100215.77      13951508.8
      3100160.66     13951545.36        3099467.     13952066.88
      3099015.12      13953003.5
#Sta/Elev= 30
  4009.7  112.41  4179.7  108.73  4539.7  107.61  4719.7  105.04  4779.7  102.14
  4829.7  103.64  4949.7  101.75  4961.3  100.94  4991.3   93.68  4997.1   89.94
  4997.3   86.47  4999.7   86.33  5002.9   86.52  5003.1   90.01  5067.4  103.03
  5187.4  102.95    5647  106.74  5717.4   99.04  5747.4   98.05  5965.2   97.97
  6025.2  100.89  6075.2  109.12  6395.2  110.83  6475.2  100.38  6585.2  100.17
  6625.2  102.55  6685.2   110.8  6765.2  109.98  6875.2  113.68  6935.2  112.76
#Mann= 9 ,-1 , 0
  4009.7     .14       0  4179.7      .1       0  4949.7     .04       0
  4961.3     .03       0  5067.4     .04       0  5187.4      .1       0
    5647    .025       0  6025.2     .99       0  6685.2     .09       0
#Block Obstruct= 2 ,-1
    5648    6075  106.77    6395    6686   110.8
Bank Sta=4961.3,5067.4
XS Rating Curve= 0
Exp/Cntr=.7,.5

Type RM Length L Ch R = 1 ,11427.  ,253,262.3,325
BEGIN DESCRIPTION:
interpolated channel - LIDAR overbanks
WEIR +/- 1600' US CYPRESSWOOD DR. - XS 1
END DESCRIPTION:
XS GIS Cut Line= 5
      3101148.67     13951504.58      3100261.92     13951448.91
      3100130.97     13951416.81      3099440.37     13951882.86
      3099001.25     13952904.07
#Sta/Elev= 30
  4022.2  110.89  4142.2   107.9  4182.2  108.86  4622.2  105.69  4802.2   101.8
  4910.7  102.52  4980.7   89.81 4996.47   89.07  4996.7    86.6 4999.52   86.04
 5002.39    86.2 5002.57   88.66  5045.5   94.08  5235.5    94.5  5295.5   102.6
  5335.5  103.56  5745.5  107.07  5825.5  101.06  5898.7   99.03  6138.7   98.09
  6178.7  100.41  6238.7  109.53  6538.7  112.48  6578.7   109.3  6628.7  100.65
  6668.7  100.17  6708.7  103.17  6758.7  110.48  6888.7  109.78  6990.3  113.32
#Mann= 7 ,-1 , 0
  4022.2     .12       0  4182.2      .1       0  4910.7     .04       0
  5045.5     .04       0  5335.5      .1       0  6238.7     .12       0
  6538.7      .1       0
#Block Obstruct= 2 ,-1
 5749.31  6225.9  107.13 6534.44 6782.37  111.26
Bank Sta=4910.7,5045.5
XS Rating Curve= 0
Exp/Cntr=.3,.1

Type RM Length L Ch R = 1 ,11164.70,377,387.7,459
BEGIN DESCRIPTION:
Cross Section K120-00-00-X05; Swampy low area on right of creek VRR
END DESCRIPTION:
XS GIS Cut Line= 4
      3101226.68      13951429.7      3100355.98     13951218.28
      3100215.27     13951165.01      3098858.53      13950819.6
#Sta/Elev= 30
  4012.9   110.6  4092.9     111  4212.9   107.2  4242.9   108.3  4292.9   107.1
  4412.9   106.7  4442.9   105.3  4562.9   106.3  4782.9   104.4  4842.9   101.3
  4862.9   101.6    4905  102.57  4926.6  100.24  4937.9   97.83  4996.5   86.68
  4999.1   85.35  5042.8   94.47  5068.5   94.31  5109.4    91.9  5189.4    92.8
  5319.4    91.4  5499.4    92.3  5529.4    94.3  5569.4   101.3  5589.4   102.9
  6079.4   108.3  6189.4   110.3  6229.4   109.5  6259.4   110.5  6459.4   110.7
#Mann= 8 ,-1 , 0
  4012.9     .14       0  4212.9     .06       0  4292.9      .1       0
  4862.9    .045       0  4937.9     .04       0  5042.8    .045       0
  5109.4     .06       0  6079.4     .12       0
Bank Sta=4937.9,5042.8
XS Rating Curve= 0
Exp/Cntr=.3,.1

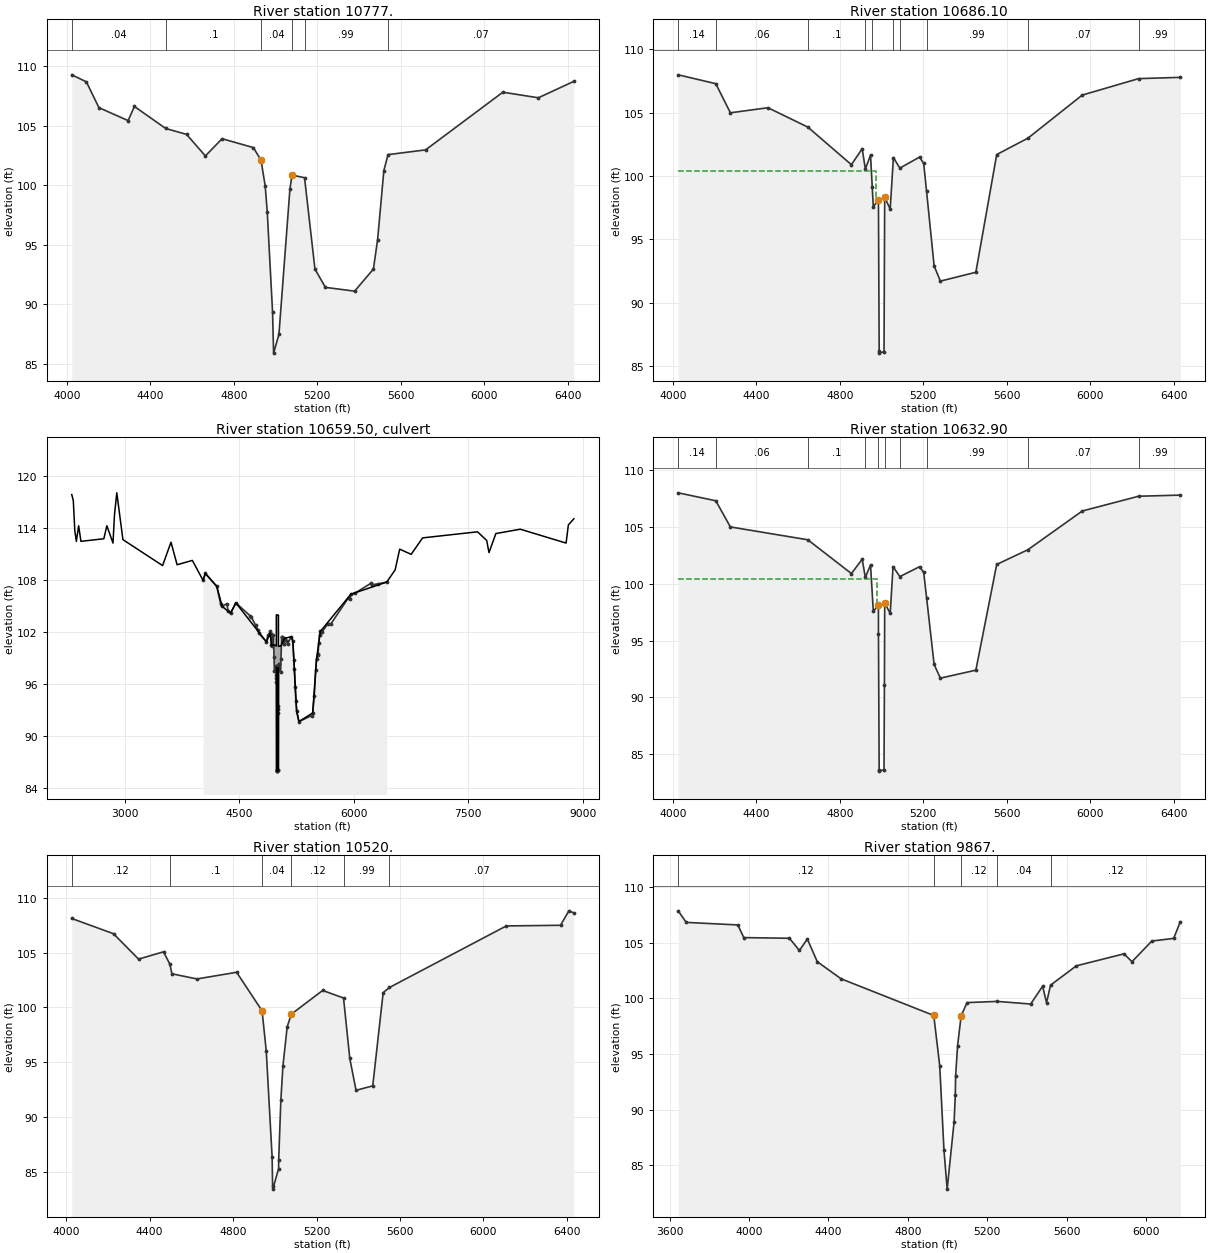
Type RM Length L Ch R = 1 ,10777.  ,90,90.9,92
BEGIN DESCRIPTION:
interpolated channel - LIDAR overbanks
CULVERT 1000' US CYPRESSWOOD - XS 4
END DESCRIPTION:
XS GIS Cut Line= 4
       3101340.2     13951230.27      3100512.96     13950884.79
      3100395.95     13950810.58      3099067.32      13950476.3
#Sta/Elev= 30
  4023.8  109.28  4093.8  108.69  4153.8  106.52  4293.8  105.43  4323.8  106.62
  4473.8  104.77  4573.8  104.27  4663.8  102.46  4743.8  103.91  4893.8  103.16
  4930.3   102.1  4950.3   99.96  4960.3   97.73 4985.67   89.33 4990.59   85.88
  5016.2   87.46  5068.8   99.67  5078.8  100.85  5138.8  100.63  5188.8   92.94
  5238.8   91.41  5378.8   91.09  5468.8   92.95  5488.8   95.41  5518.8  101.23
  5538.8  102.57  5718.8  102.97  6088.8  107.82  6258.8  107.35  6428.9  108.73
#Mann= 6 ,-1 , 0
  4023.8     .04       0  4473.8      .1       0  4930.3     .04       0
  5078.8     .12       0  5138.8     .99       0  5538.8     .07       0
Bank Sta=4930.3,5078.8
XS Rating Curve= 0
Exp/Cntr=.5,.3

Type RM Length L Ch R = 1 ,10686.10,53.2,53.2,53.2
BEGIN DESCRIPTION:
Upstream Section of Bridge/Culvert/Weir
CULVERT 1000' US CYPRESSWOOD - XS 3
END DESCRIPTION:
XS GIS Cut Line= 4
      3101391.08      13951151.6      3100561.29     13950813.12
      3100446.83     13950731.94       3099118.2      13950397.6
#Sta/Elev= 30
  4025.1  107.99  4205.1  107.29  4275.1  104.99  4455.1  105.39  4646.2  103.86
  4855.1  100.89  4906.8  102.15  4921.9  100.55  4946.8  101.65    4955   99.12
    4960   97.58  4984.7   98.08  4988.2   86.14  4988.6      86  5011.4   86.12
  5014.7   98.31    5041   97.38  5056.4  101.45  5087.3  100.62  5181.6  101.49
  5201.6  100.99  5215.4   98.78  5251.6   92.89  5281.6   91.69  5451.6   92.39
  5551.6  101.69  5701.6  102.99  5961.6  106.39  6231.6  107.69  6431.6  107.79
#Mann= 10 ,-1 , 0
  4025.1     .14       0  4205.1     .06       0  4646.2      .1       0
  4921.9    .045       0    4955     .02       0  5056.4     .06       0
  5087.3     .12       0  5215.4     .99       0  5701.6     .07       0
  6231.6     .99       0
#XS Ineff= 2 , 0
       0  4974.7  100.42  5024.7       0    91.7
Permanent Ineff=
       F       F
Bank Sta=4984.7,5014.7
XS Rating Curve= 0
Exp/Cntr=.5,.3

Type RM Length L Ch R = 2 ,10659.50,,,
BEGIN DESCRIPTION:
CULVERT 1000' US CYPRESSWOOD
Structure ID: K120-00-00-S2-1
END DESCRIPTION:
Bridge Culvert--1,0,-1,-1, 0
Deck Dist Width WeirC Skew NumUp NumDn MinLoCord MaxHiCord MaxSubmerge Is_Ogee
10,32,3,0, 60, 60, , , .95, 0, ,,,
  2305.1  2325.1  2345.1  2365.1  2395.1  2425.1  2725.1  2765.1  2845.1  2865.1
  2895.1  2975.1  3495.1  3605.1  3685.1  3885.1  4025.1  4055.1  4205.1  4275.1
  4385.1  4455.1  4855.1  4905.1  4923.4    4955    4960  4984.8 4985.09  4985.2
  4988.2  4988.6  5011.4  5013.3 5013.41  5014.7    5041    5046  5090.5  5181.6
  5201.6  5251.6  5281.6  5461.6  5511.6  5561.6  5961.6  6431.6  6541.6  6601.6
  6751.6  6901.6  7621.6  7741.6  7771.6  7861.6  8181.6  8781.6  8811.6  8883.3
   117.9   117.2   113.7   112.5   114.3   112.5   112.8   114.3   112.3   115.6
   118.1   112.7   109.7   112.4   109.8   110.3     108   108.8   107.3     105
   104.2   105.4   100.9   101.9  100.46  100.57  100.54  100.42  100.42  104.02
  104.02  104.02  103.98  103.98  100.38  100.37  100.42  100.43   101.3   101.5
     101    92.9    91.7    92.7    98.9   102.1   106.4   107.8   109.2   111.6
     111   112.9   113.6   112.6   111.2   113.4   113.9   112.3   114.4   115.1
   117.9   117.2   113.7   112.5   114.3   112.5   112.8   114.3   112.3   115.6
   118.1   112.7   109.7   112.4   109.8   110.3     108   108.8   107.3     105
   104.2   105.4   100.9   101.9  100.41   99.13   97.59   98.09   97.07   96.69
   86.15   86.01   86.13   93.15   93.55   98.32   97.39   98.89   101.3   101.5
     101    92.9    91.7    92.7    98.9   102.1   106.4   107.8   109.2   111.6
     111   112.9   113.6   112.6   111.2   113.4   113.9   112.3   114.4   115.1
  2305.1  2325.1  2345.1  2365.1  2395.1  2425.1  2725.1  2765.1  2845.1  2865.1
  2895.1  2975.1  3495.1  3605.1  3685.1  3885.1  4025.1  4055.1  4205.1  4275.1
  4385.1  4455.1  4855.1  4905.1  4923.4    4955    4960  4984.8 4985.09  4985.2
  4988.2  4988.6  5011.4  5013.3 5013.41  5014.7    5041    5046  5090.5  5181.6
  5201.6  5251.6  5281.6  5461.6  5511.6  5561.6  5961.6  6431.6  6541.6  6601.6
  6751.6  6901.6  7621.6  7741.6  7771.6  7861.6  8181.6  8781.6  8811.6  8883.3
   117.9   117.2   113.7   112.5   114.3   112.5   112.8   114.3   112.3   115.6
   118.1   112.7   109.7   112.4   109.8   110.3     108   108.8   107.3     105
   104.2   105.4   100.9   101.9  100.46  100.57  100.54  100.42  100.42  104.02
  104.02  104.02  103.98  103.98  100.38  100.37  100.42  100.43   101.3   101.5
     101    92.9    91.7    92.7    98.9   102.1   106.4   107.8   109.2   111.6
     111   112.9   113.6   112.6   111.2   113.4   113.9   112.3   114.4   115.1
  115.41  114.71  111.21  110.01  111.81  110.01  110.31  111.81  109.81  113.11
  115.61  110.21  107.21  109.91  107.31  107.81  105.51  106.31  104.81  102.51
  101.71  102.91   98.41   99.41   97.92   96.64    95.1    95.6   94.58    94.2
   83.66   83.52   83.64   90.66   91.06   95.83    94.9    96.4   98.81   99.01
   98.51   90.41   89.21   90.21   96.41   99.61  103.91  105.31  106.71  109.11
  108.51  110.41  111.11  110.11  108.71  110.91  111.41  109.81  111.91  112.61
BR Coef= 1 , 0 , 0 ,1.25, 0 ,,,.8,-1,2,0,
WSPro=,,,, 1 ,,,, 0 ,,,, 0 ,,,,-1 ,-1 ,-1 , 0 , 0 , 0 , 0 , 0
Culvert=2,12,12,32,.015,.5,1,8,1,85.98,4992.5,83.57,4992.5,Culvert #1  , 0 ,10
Culvert Bottom n=.015
Culvert=2,12,12,32,.015,.5,1,8,1,85.98,5006.9,83.61,5006.9,Culvert #2  , 0 ,10
Culvert Bottom n=.015
BR U #Sta/Elev= 83
  4025.1     108  4055.1   108.8  4205.1   107.3  4255.1   105.3  4275.1     105
  4335.1   105.3  4355.1   104.5  4385.1   104.2  4455.1   105.4  4646.2  103.87
  4655.1   103.8  4715.1   102.8  4745.1   102.3  4755.1   101.9  4855.1   100.9
  4875.1   101.7  4905.1   101.9  4906.8  102.16    4908  101.92    4909  101.82
  4921.9  100.56  4923.4  100.41  4930.2  101.27  4946.8  101.66    4955   99.13
    4960   97.59  4984.7   98.09  4984.8   98.09 4985.09   97.07  4985.2   96.69
 4985.31    96.3  4988.2   86.15  4988.5   86.14  4988.6   86.01  4998.3   86.05
  4999.2   86.05  5011.3   86.11  5011.4   86.13 5013.19   92.74  5013.3   93.15
 5013.41   93.55  5014.7   98.32  5015.1   98.31    5041   97.39    5046   98.89
  5054.7  101.51  5056.4  101.46  5087.3  100.63  5087.6  100.62  5089.9  101.16
  5090.5   101.3  5097.1  101.24  5123.6  101.01  5131.6   100.7  5181.6   101.5
  5201.6     101  5215.4   98.79  5221.6    97.8  5231.6    95.7  5241.6    94.1
  5251.6    92.9  5281.6    91.7  5451.6    92.4  5461.6    92.7  5481.6    94.6
  5501.6    97.7  5511.6    98.9  5531.6    99.4    5532   99.46  5541.6   100.8
  5551.6   101.7  5561.6   102.1  5581.6     102  5661.6     103  5701.6     103
  5931.6     106  5951.6   105.9  5961.6   106.4  6011.6   106.5  6231.6   107.7
  6241.6   107.5  6321.6   107.6  6431.6   107.8
BR U #Mann= 10
  4025.1     .14  4205.1     .06  4646.2      .1  4921.9    .045    4955     .02
  5056.4     .06  5087.3     .12  5215.4     .99  5701.6     .07  6231.6     .99
BR U Banks=4984.7,5014.7
BR D #Sta/Elev= 83
  4025.1     108  4055.1   108.8  4205.1   107.3  4255.1   105.3  4275.1     105
  4335.1   105.3  4355.1   104.5  4385.1   104.2  4455.1   105.4  4646.2  103.87
  4655.1   103.8  4715.1   102.8  4745.1   102.3  4755.1   101.9  4855.1   100.9
  4875.1   101.7  4905.1   101.9  4906.8  102.16    4908  101.92    4909  101.82
  4921.9  100.56  4923.4  100.41  4930.2  101.27  4946.8  101.66    4955   99.13
    4960   97.59  4984.7    95.6  4984.8    95.6 4985.09   94.58  4985.2    94.2
 4985.31   93.81  4988.2   83.66  4988.5   83.65  4988.6   83.52  4998.3   83.56
  4999.2   83.56  5011.3   83.62  5011.4   83.64 5013.19   90.25  5013.3   90.66
 5013.41   91.06  5014.7   95.83  5015.1   98.31    5041   97.39    5046   98.89
  5054.7  101.51  5056.4  101.46  5087.3  100.63  5087.6  100.62  5089.9  101.16
  5090.5   101.3  5097.1  101.24  5123.6  101.01  5131.6   100.7  5181.6   101.5
  5201.6     101  5215.4   98.79  5221.6    97.8  5231.6    95.7  5241.6    94.1
  5251.6    92.9  5281.6    91.7  5451.6    92.4  5461.6    92.7  5481.6    94.6
  5501.6    97.7  5511.6    98.9  5531.6    99.4    5532   99.46  5541.6   100.8
  5551.6   101.7  5561.6   102.1  5581.6     102  5661.6     103  5701.6     103
  5931.6     106  5951.6   105.9  5961.6   106.4  6011.6   106.5  6231.6   107.7
  6241.6   107.5  6321.6   107.6  6431.6   107.8
BR D #Mann= 10
  4025.1     .14  4205.1     .06  4646.2      .1  4921.9    .045    4955     .02
  5056.4     .06  5087.3     .12  5215.4     .99  5701.6     .07  6231.6     .99
BR D Banks=4984.7,5014.7
BC Design=,, 0 ,, 0 ,,,,,,
BC HTab HWMax=108.79

Type RM Length L Ch R = 1 ,10632.90,119,112.9,103
BEGIN DESCRIPTION:
Downstream Section of Bridge/Culvert/Weir
CULVERT 1000' US CYPRESSWOOD - XS 2
END DESCRIPTION:
XS GIS Cut Line= 4
       3101418.9      13951107.2      3100591.24     13950769.58
      3100475.61     13950687.57      3099143.35      13950352.3
#Sta/Elev= 30
  4025.1  107.99  4205.1  107.29  4275.1  104.99  4646.2  103.86  4855.1  100.89
  4906.8  102.15  4921.9  100.55  4946.8  101.65    4960   97.58  4984.7   98.08
  4984.8   95.59  4988.2   83.65  4988.6   83.51  5011.4   83.63 5013.41   91.05
  5014.7   98.31    5041   97.38  5054.7   101.5  5087.3  100.62  5181.6  101.49
  5201.6  100.99  5215.4   98.78  5251.6   92.89  5281.6   91.69  5451.6   92.39
  5551.6  101.69  5701.6  102.99  5961.6  106.39  6231.6  107.69  6431.6  107.79
#Mann= 10 ,-1 , 0
  4025.1     .14       0  4205.1     .06       0  4646.2      .1       0
  4921.9    .045       0  4984.7     .04       0  5014.7    .045       0
  5087.3     .12       0  5215.4     .99       0  5701.6     .07       0
  6231.6     .99       0
#XS Ineff= 2 , 0
       0 4978.03  100.42 5021.37       0    91.7
Permanent Ineff=
       F       F
Bank Sta=4984.7,5014.7
XS Rating Curve= 0
Exp/Cntr=.5,.3

Type RM Length L Ch R = 1 ,10520.  ,652,653,658
BEGIN DESCRIPTION:
interpolated channel - LIDAR overbanks
CULVERT 1000' US CYPRESSWOOD - XS 1
END DESCRIPTION:
XS GIS Cut Line= 4
      3101472.11     13951021.64      3100647.75      13950655.2
      3100528.81     13950601.99      3099196.56     13950266.79
#Sta/Elev= 30
  4026.9  108.12  4226.9  106.73  4346.9  104.41  4466.9  105.08  4496.9  103.95
  4506.9  103.07  4626.9   102.6  4816.9  103.21    4939   99.69    4959   96.01
 4987.11   86.33 4989.31   83.72 4990.47   83.41 5018.23   85.29 5018.45   86.05
    5029   91.56    5039   94.68  5059.3   98.23  5079.3   99.39  5229.3  101.55
  5329.3  100.86  5359.3   95.34  5389.3   92.43  5469.3   92.84  5519.3  101.35
  5549.3  101.82  6109.3  107.44  6369.3   107.5  6409.3  108.82  6433.1  108.63
#Mann= 6 ,-1 , 0
  4026.9     .12       0  4496.9      .1       0    4939     .04       0
  5079.3     .12       0  5329.3     .99       0  5549.3     .07       0
Bank Sta=4939,5079.3
XS Rating Curve= 0
Exp/Cntr=.3,.1

Type RM Length L Ch R = 1 ,9867.   ,80,156.7,265
BEGIN DESCRIPTION:
interpolated channel - LIDAR overbanks
E. CYPRESSWOOD - XS 4
END DESCRIPTION:
XS GIS Cut Line= 5
       3101664.8     13950800.27      3100755.13     13950266.16
        3100770.       13950045.      3100641.83     13949971.34
      3099603.52      13949597.8
#Sta/Elev= 30
  3643.6  107.89  3683.6  106.85  3943.6  106.62  3973.6  105.48  4203.6  105.42
  4253.6  104.32  4293.6  105.35  4343.6  103.31  4463.6  101.77  4930.1   98.47
  4960.1   93.95 4981.53   86.34 4997.55   82.84 5032.55   88.91 5038.58   91.31
  5040.1   93.01  5050.1   95.76    5068   98.45    5098   99.63    5250  99.738
    5418    99.5    5478   101.1    5498   99.62    5518   101.2    5648  102.94
    5888  104.02    5928  103.31    6028  105.17    6138  105.41  6171.4  106.91
#Mann= 5 ,-1 , 0
  3643.6     .12       0  4930.1     .04       0    5068     .12       0
    5250     .04       0    5518     .12       0
Bank Sta=4930.1,5068
XS Rating Curve= 0
Exp/Cntr=.5,.3

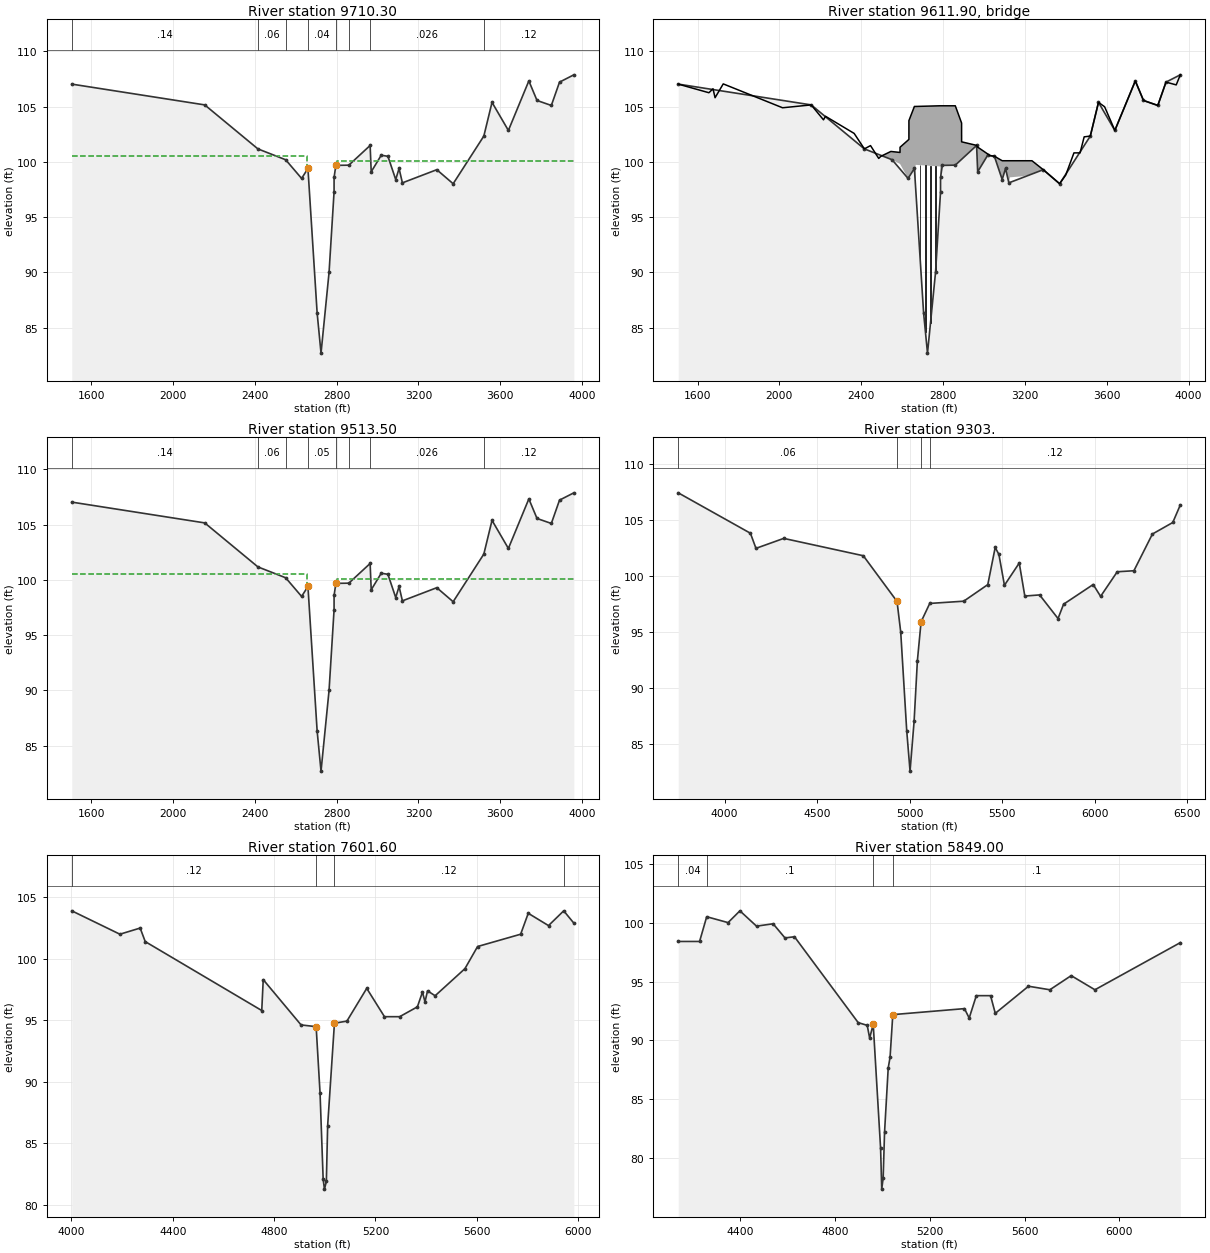
Type RM Length L Ch R = 1 ,9710.30 ,196.8,196.8,196.8
BEGIN DESCRIPTION:
Upstream Section of Bridge/Culvert/Weir
E. CYPRESSWOOD - XS 3
END DESCRIPTION:
XS GIS Cut Line= 6
      3101713.36      13950714.6       3100803.7     13950180.58
      3100760.59     13949695.53      3100728.25     13949490.74
      3100577.35     13949038.03      3099931.35      13948859.9
#Sta/Elev= 30
  1505.4  107.03  2155.4  105.15  2415.4  101.17 2550.87  100.19 2628.97    98.5
 2659.91    99.4 2704.84   86.34  2723.9    82.7 2763.17      90 2787.63   97.28
 2787.74   98.59  2796.4   99.68 2859.79    99.7 2963.93  101.48 2969.21    99.1
 3018.23   100.6 3050.91   100.5 3089.03    98.4 3105.37    99.4 3121.71    98.1
  3289.8   99.29  3369.8   98.02  3519.8  102.33  3559.8  105.38  3639.8  102.84
  3739.8  107.32  3779.8  105.55  3849.8   105.1  3889.8  107.21  3959.8  107.87
#Mann= 8 ,-1 , 0
  1505.4     .14       0  2415.4     .06       0 2550.87     .07       0
 2659.91     .04       0  2796.4     .04       0 2859.79     .09       0
 2963.93    .026       0  3519.8     .12       0
#XS Ineff= 2 , 0
       02656.275   100.52800.027       0   100.1
Permanent Ineff=
       F       F
#Block Obstruct= 1 ,-1
    5442    6081  101.44
Bank Sta=2659.91,2796.4
XS Rating Curve= 0
Exp/Cntr=.5,.3

Type RM Length L Ch R = 3 ,9611.90 ,,,
BEGIN DESCRIPTION:
E. CYPRESSWOOD
Structure ID: K120-00-00-S2
END DESCRIPTION:
Bridge Culvert--1,0,-1,-1, 0
Deck Dist Width WeirC Skew NumUp NumDn MinLoCord MaxHiCord MaxSubmerge Is_Ogee
10,167,2.6,57, 60, 60, , , .95, 0, ,,,
  1505.4  1655.4  1675.4  1685.4  1725.4  2015.4  2155.4  2215.4  2225.4  2365.4
  2415.4  2445.4  2485.4 2495.81 2544.83 2589.54  2589.7    2633 2633.06 2659.91
 2664.65 2664.76 2665.91 2665.95 2786.04  2786.1 2787.63 2787.74  2796.4 2859.79
 2890.62 2890.68 2963.93 2969.21 3001.89 3018.23 3029.12 3050.91 3089.03 3105.37
 3121.71 3127.15 3190.99 3234.56  3289.8  3369.8  3399.8  3439.8  3469.8  3489.8
  3519.8  3559.8  3589.8  3639.8  3739.8  3779.8  3849.8  3889.8  3939.8  3959.8
  107.03  106.25  106.61   105.8  107.05  104.89  105.15   103.8  104.12  102.57
  101.17  101.47  100.31   100.5  100.94  100.85  101.32  102.03  103.73  105.01
  105.01  105.01  105.01  105.01  105.07  105.07  105.07  105.07  105.07  105.07
  103.51  101.81  101.49  101.33  100.92  100.71  100.57  100.51   100.1   100.1
   100.1   100.1   100.1   100.1   99.29   98.02   98.81  100.81  100.81  102.26
  102.33  105.38  104.98  102.84  107.32  105.55   105.1  107.21  106.96  107.87
  107.03  106.25  106.61   105.8  107.05  104.89  105.15   103.8  104.12  102.57
  101.17  101.47  100.31      99     100   99.81   99.81      98      98    99.4
   98.12   98.62   98.28   99.73   99.58   97.02   97.28   98.59   99.68    99.7
   99.91   99.91  101.48    99.1    99.5   100.6    99.8   100.5    98.4    99.4
    98.1    98.6    98.7      98   99.29   98.02   98.81  100.81  100.81  102.26
  102.33  105.38  104.98  102.84  107.32  105.55   105.1  107.21  106.96  107.87
  1505.4  1655.4  1675.4  1685.4  1725.4  2015.4  2155.4  2215.4  2225.4  2365.4
  2415.4  2445.4  2485.4 2495.81 2544.83 2589.54  2589.7    2633 2633.06 2659.91
 2664.65 2664.76 2665.91 2665.95 2786.04  2786.1 2787.63 2787.74  2796.4 2859.79
 2890.62 2890.68 2963.93 2969.21 3001.89 3018.23 3029.12 3050.91 3089.03 3105.37
 3121.71 3127.15 3190.99 3234.56  3289.8  3369.8  3399.8  3439.8  3469.8  3489.8
  3519.8  3559.8  3589.8  3639.8  3739.8  3779.8  3849.8  3889.8  3939.8  3959.8
  107.03  106.25  106.61   105.8  107.05  104.89  105.15   103.8  104.12  102.57
  101.17  101.47  100.31   100.5  100.94  100.85  101.32  102.03  103.73  105.01
  105.01  105.01  105.01  105.01  105.07  105.07  105.07  105.07  105.07  105.07
  103.51  101.81  101.49  101.33  100.92  100.71  100.57  100.51   100.1   100.1
   100.1   100.1   100.1   100.1   99.29   98.02   98.81  100.81  100.81  102.26
  102.33  105.38  104.98  102.84  107.32  105.55   105.1  107.21  106.96  107.87
  107.03  106.25  106.61   105.8  107.05  104.89  105.15   103.8  104.12  102.57
  101.17  101.47  100.31      99     100   99.81   99.81      98      98    99.4
   98.12   98.62   98.28   99.73   99.58   97.02   97.28   98.59   99.68    99.7
   99.91   99.91  101.48    99.1    99.5   100.6    99.8   100.5    98.4    99.4
    98.1    98.6    98.7      98   99.29   98.02   98.81  100.81  100.81  102.26
  102.33  105.38  104.98  102.84  107.32  105.55   105.1  107.21  106.96  107.87
Pier Skew, UpSta & Num, DnSta & Num=  ,2688.828, 2 ,2688.828, 2 , 0 , 0 , 0 ,,
     1.3     1.3
   90.34  100.71
     1.3     1.3
   90.45  100.82
Pier Skew, UpSta & Num, DnSta & Num=  ,2713.664, 2 ,2713.664, 2 , 0 , 0 , 0 ,,
     1.3     1.3
   83.78  100.68
     1.3     1.3
   83.89  100.79
Pier Skew, UpSta & Num, DnSta & Num=  ,2738.608, 2 ,2738.608, 2 , 0 , 0 , 0 ,,
     1.3     1.3
   84.56  100.61
     1.3     1.3
   84.67  100.72
Pier Skew, UpSta & Num, DnSta & Num=  ,2763.172, 2 ,2763.172, 2 , 0 , 0 , 0 ,,
     1.3     1.3
   88.97  100.56
     1.3     1.3
   89.08  100.67
BR Coef= 1 , 1 , 1 ,1.25, 0 ,,,.8,0,2,0,
WSPro=,,,, 1 ,,,, 0 ,,,, 0 ,,,,-1 ,-1 ,-1 , 0 , 0 , 0 , 0 , 0
BC Design=,, 0 ,, 0 ,,,,,,
BC HTab HWMax=107.87

Type RM Length L Ch R = 1 ,9513.50 ,301,210.5,119
BEGIN DESCRIPTION:
Downstream Section of Bridge/Culvert/Weir
E. CYPRESSWOOD - XS 2
***Bridge deck has been skewed 57 degrees***
END DESCRIPTION:
XS GIS Cut Line= 6
      3101797.13      13950557.8      3100896.35     13950028.98
      3100854.08     13949553.52      3100821.38     13949346.42
      3100666.58     13948882.01       3100010.3      13948701.1
#Sta/Elev= 30
  1505.4  107.03  2155.4  105.15  2415.4  101.17 2550.87  100.19 2628.97    98.5
 2659.91    99.4 2704.84   86.34  2723.9    82.7 2763.17      90 2787.63   97.28
 2787.74   98.59  2796.4   99.68 2859.79    99.7 2963.93  101.48 2969.21    99.1
 3018.23   100.6 3050.91   100.5 3089.03    98.4 3105.37    99.4 3121.71    98.1
  3289.8   99.29  3369.8   98.02  3519.8  102.33  3559.8  105.38  3639.8  102.84
  3739.8  107.32  3779.8  105.55  3849.8   105.1  3889.8  107.21  3959.8  107.87
#Mann= 8 ,-1 , 0
  1505.4     .14       0  2415.4     .06       0 2550.87     .07       0
 2659.91     .05       0  2796.4     .04       0 2859.79     .09       0
 2963.93    .026       0  3519.8     .12       0
#XS Ineff= 2 , 0
       02656.275   100.52800.027       0   100.1
Permanent Ineff=
       F       F
Bank Sta=2659.91,2796.4
XS Rating Curve= 0
Skew Angle= 57
Exp/Cntr=.5,.3

Type RM Length L Ch R = 1 ,9303.   ,1751,1701.4,1675
BEGIN DESCRIPTION:
interpolated channel - LIDAR overbanks
E. CYPRESSWOOD - XS 1
END DESCRIPTION:
XS GIS Cut Line= 6
      3102049.79     13950125.23        3101040.       13949550.
      3100894.61     13949468.37      3100869.96     13949256.21
      3100715.16     13948791.81      3100058.88     13948610.94
#Sta/Elev= 30
  3749.9   107.4  4139.9  103.79  4169.9  102.44  4319.9  103.33  4749.9  101.78
    4932    97.7    4952   94.96 4984.34   86.16 5002.38   82.54 5024.27   86.99
    5042    92.4    5062   95.88  5108.8   97.52  5292.4   97.72  5422.4    99.2
  5462.4  102.52  5482.4   101.9  5512.4   99.14  5592.4  101.13  5622.4   98.18
  5702.4   98.28  5801.9   96.17  5831.9   97.45  5991.9   99.21  6031.9   98.15
  6121.9  100.35  6211.9  100.44  6311.9  103.72  6421.9  104.75  6462.6  106.32
#Mann= 4 ,-1 , 0
  3749.9     .06       0    4932     .05       0    5062     .04       0
  5108.8     .12       0
Bank Sta=4932,5062
XS Rating Curve= 0
Exp/Cntr=.3,.1

Type RM Length L Ch R = 1 ,7601.60 ,1790,1752.6,1665
BEGIN DESCRIPTION:
Cross Section K120-00-00-X4
END DESCRIPTION:
XS GIS Cut Line= 5
      3101746.81       13948576.      3100918.97     13948163.47
      3100800.14     13948112.13      3100349.47     13947901.27
       3099923.6      13947961.1
#Sta/Elev= 30
  4001.3   103.9  4191.3     102  4271.3   102.5  4291.3   101.4  4751.3    95.8
  4757.1   98.31  4906.5   94.63    4966   94.49  4981.4    89.1  4993.7   82.08
  4998.9   81.29  5006.3   81.91  5011.4   86.44  5038.2   94.77  5087.4   94.94
  5165.7    97.6  5235.7    95.3  5295.7    95.3  5365.7    96.1  5385.7    97.3
  5395.7    96.5  5405.7    97.4  5435.7      97  5553.3    99.2  5603.3     101
  5773.3     102  5803.3   103.7  5883.3   102.7  5943.3   103.9  5983.3   102.9
#Mann= 4 ,-1 , 0
  4001.3     .12       0    4966    .055       0  5038.2     .12       0
  5943.3      .1       0
Bank Sta=4966,5038.2
XS Rating Curve= 0
Exp/Cntr=.3,.1

Type RM Length L Ch R = 1 ,5849.00 ,1295,1307,1321
BEGIN DESCRIPTION:
Cross Section K120-00-00-X3
END DESCRIPTION:
XS GIS Cut Line= 4
      3101900.16      13946639.7      3101130.64     13946445.17
      3100992.42     13946481.43      3099932.14      13946999.3
#Sta/Elev= 30
  4139.8    98.4  4229.8    98.4  4259.8   100.5  4349.8     100  4399.8     101
  4469.8    99.7  4539.8    99.9  4589.8    98.7  4629.8    98.8  4898.5   91.51
  4936.5   91.28  4946.7    90.2  4961.8   91.37  4992.9   80.84  4997.7   77.38
  5003.7   78.32  5009.6   82.22    5025   87.66  5032.8   88.57  5044.3   92.19
  5346.4    92.7  5366.4    91.9  5396.4    93.8  5456.4    93.8  5476.4    92.3
  5616.4    94.6  5706.4    94.3  5796.4    95.5  5896.4    94.3  6256.4    98.3
#Mann= 4 ,-1 , 0
  4139.8     .04       0  4259.8      .1       0  4961.8     .04       0
  5044.3      .1       0
Bank Sta=4961.8,5044.3
XS Rating Curve= 0
Exp/Cntr=.3,.1

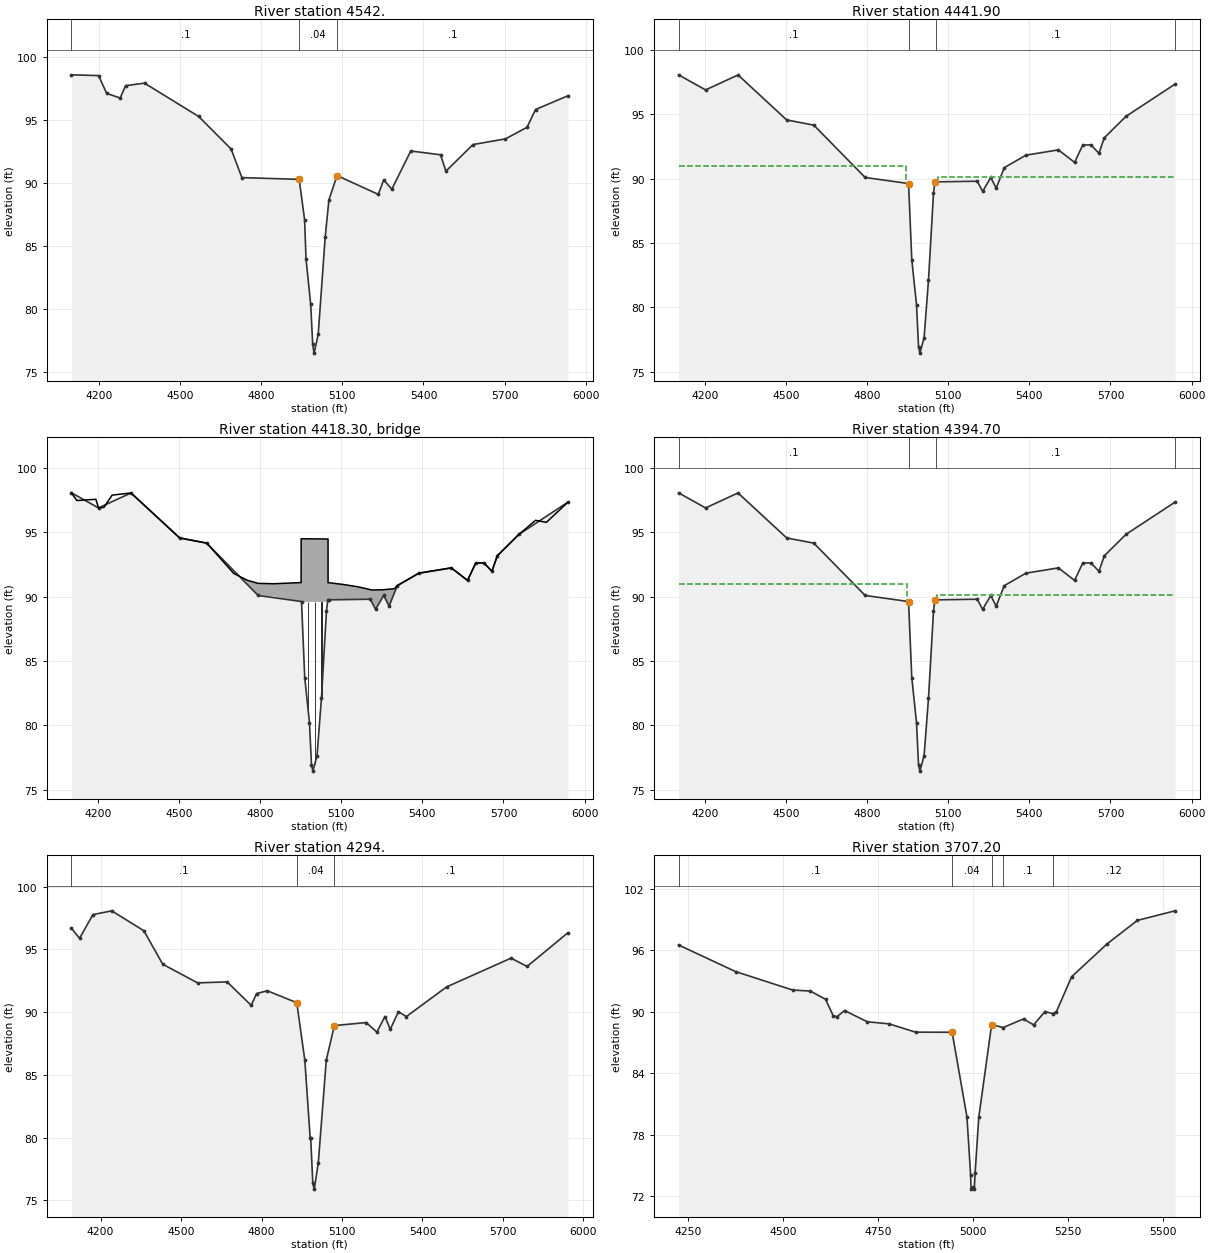
Type RM Length L Ch R = 1 ,4542.   ,99.22,100.1,101
BEGIN DESCRIPTION:
interpolated channel - LIDAR overbanks
LOCKRIDGE DR. - XS 4
END DESCRIPTION:
XS GIS Cut Line= 5
      3101898.08     13945335.15      3101138.91     13945148.33
      3100927.86     13945172.88      3100254.61     13945431.83
      3100143.85     13945477.81
#Sta/Elev= 30
  4098.7    98.6  4198.7   98.54  4228.7   97.13  4278.7   96.76  4298.7   97.74
  4368.7   97.94  4568.7    95.3  4688.7   92.72  4728.7   90.45  4940.5   90.31
  4960.5   87.11 4965.77   84.01 4983.09   80.39 4990.52   77.22 4995.56   76.53
 5010.89   78.02 5036.68   85.73  5050.5   88.69  5080.5   90.61    5233   89.12
    5253   90.27    5283   89.53    5353   92.56    5463   92.26    5483   90.96
    5583   93.07    5703   93.52    5783   94.44  5814.3   95.85  5934.3   96.94
#Mann= 3 ,-1 , 0
  4098.7      .1       0  4940.5     .04       0  5080.5      .1       0
Bank Sta=4940.5,5080.5
XS Rating Curve= 0
Exp/Cntr=.5,.3

Type RM Length L Ch R = 1 ,4441.90 ,47.2,47.2,47.2
BEGIN DESCRIPTION:
Upstream Section of Bridge/Culvert/Weir
LOCKRIDGE DR. - XS 3
END DESCRIPTION:
XS GIS Cut Line= 5
       3101884.2      13945235.6      3101125.03     13945048.87
      3100913.98     13945073.43      3100240.73     13945332.37
      3100129.97      13945378.3
#Sta/Elev= 30
    4103   98.04    4203   96.87    4323   98.03    4503   94.54    4603   94.14
    4793   90.08  4953.4   89.61  4965.3   83.72  4982.8   80.22  4990.3   76.97
  4995.4   76.46  5010.9   77.67  5027.1   82.11  5045.6   88.85  5050.6   89.75
  5054.1   89.74  5207.3   89.79  5227.3      89  5257.3   90.08  5277.3   89.25
  5307.3   90.84  5387.3   91.81  5507.3   92.22  5567.3   91.25  5597.3   92.59
  5627.3   92.61  5657.3   91.96  5677.3   93.16  5757.3   94.82  5938.6   97.32
#Mann= 4 ,-1 , 0
    4103      .1       0  4953.4     .04       0  5054.1      .1       0
  5938.6     .06       0
#XS Ineff= 2 , 0
       0  4943.4   90.99  5060.6       0   90.08
Permanent Ineff=
       F       F
Bank Sta=4953.4,5050.6
XS Rating Curve= 0
Exp/Cntr=.5,.3

Type RM Length L Ch R = 3 ,4418.30 ,,,
BEGIN DESCRIPTION:
LOCKRIDGE DR.
Structure ID: K120-00-00-S1
END DESCRIPTION:
Bridge Culvert--1,0,-1,-1, 0
Deck Dist Width WeirC Skew NumUp NumDn MinLoCord MaxHiCord MaxSubmerge Is_Ogee
10,24,2.6,0, 48, 48, , , .95, 0, ,,,
    4103    4123    4193    4203    4223    4253    4323    4503    4603    4703
  4727.2  4742.7  4744.1  4754.2    4793  4850.9    4952  4952.1  5051.5 5051.61
    5053 5053.09  5053.2  5053.3  5054.1  5105.5  5106.2  5159.9  5160.6  5208.3
  5211.5  5219.1  5242.5  5252.8  5253.2  5297.2  5307.3  5387.3  5507.3  5567.3
  5597.3  5627.3  5657.3  5677.3  5757.3  5818.6  5858.6  5938.6
   98.04   97.44   97.54   96.87   96.91   97.86   98.03   94.54   94.14   91.79
   91.53   91.37   91.35   91.25   91.02   90.99   91.08   94.48   94.46   91.06
   91.07   91.07   91.07   91.07   91.07   90.94   90.94   90.76   90.76   90.53
   90.51   90.51   90.52   90.52   90.52   90.61   90.84   91.81   92.22   91.25
   92.59   92.61   91.96   93.16   94.82   95.91   95.75   97.32
   98.04   97.44   97.54   96.87   96.91   97.86   98.03   94.54   94.14   91.79
      91      90      90      90      90      90   89.58   89.58   89.58   89.58
   89.58   89.58   89.58   89.58   89.58   89.58   89.58   89.31   89.31   89.31
   89.31      89      89      89      89      89   89.31   89.31   89.31   91.25
   92.59   92.61   91.96   93.16   94.82   95.91   95.75   97.32
    4103    4123    4193    4203    4223    4253    4323    4503    4603    4703
  4727.2  4742.7  4744.1  4754.2    4793  4850.9    4952  4952.1  5051.5 5051.61
    5053 5053.09  5053.2  5053.3  5054.1  5105.5  5106.2  5159.9  5160.6  5208.3
  5211.5  5219.1  5242.5  5252.8  5253.2  5297.2  5307.3  5387.3  5507.3  5567.3
  5597.3  5627.3  5657.3  5677.3  5757.3  5818.6  5858.6  5938.6
   98.04   97.44   97.54   96.87   96.91   97.86   98.03   94.54   94.14   91.79
   91.53   91.37   91.35   91.25   91.02   90.99   91.08   94.48   94.46   91.06
   91.07   91.07   91.07   91.07   91.07   90.94   90.94   90.76   90.76   90.53
   90.51   90.51   90.52   90.52   90.52   90.61   90.84   91.81   92.22   91.25
   92.59   92.61   91.96   93.16   94.82   95.91   95.75   97.32
   98.04   97.44   97.54   96.87   96.91   97.86   98.03   94.54   94.14   91.79
      91      90      90      90      90      90   89.58   89.58   89.58   89.58
   89.58   89.58   89.58   89.58   89.58   89.58   89.58   89.31   89.31   89.31
   89.31      89      89      89      89      89   89.31   89.31   89.31   91.25
   92.59   92.61   91.96   93.16   94.82   95.91   95.75   97.32
Pier Skew, UpSta & Num, DnSta & Num=  ,4977.6, 2 ,4977.6, 2 , 0 , 0 , 0 ,,
     1.5     1.5
   79.77   90.56
     1.5     1.5
   80.26   91.05
Pier Skew, UpSta & Num, DnSta & Num=  ,5002.7, 2 ,5002.7, 2 , 0 , 0 , 0 ,,
     1.5     1.5
   75.96   90.57
     1.5     1.5
   76.45   91.06
Pier Skew, UpSta & Num, DnSta & Num=  ,5027, 2 ,5027, 2 , 0 , 0 , 0 ,,
     1.5     1.5
   80.93   90.56
     1.5     1.5
   81.42   91.05
BR Coef= 1 , 1 , 1 ,1.25, 0 ,,,.8,0,2,0,
WSPro=,,,, 1 ,,,, 0 ,,,, 0 ,,,,-1 ,-1 ,-1 , 0 , 0 , 0 , 0 , 0
BC Design=,, 0 ,, 0 ,,,,,,
BC HTab HWMax=98.04

Type RM Length L Ch R = 1 ,4394.70 ,100,100.7,101
BEGIN DESCRIPTION:
Downstream Section of Bridge/Culvert/Weir
LOCKRIDGE DR. - XS 2
END DESCRIPTION:
XS GIS Cut Line= 5
      3101892.51      13945189.8      3101125.37      13945001.5
      3100908.23     13945026.77      3100228.91     13945288.04
      3100122.46      13945330.1
#Sta/Elev= 30
    4103   98.04    4203   96.87    4323   98.03    4503   94.54    4603   94.14
    4793   90.08  4953.4   89.61  4965.3   83.72  4982.8   80.22  4990.3   76.97
  4995.4   76.46  5010.9   77.67  5027.1   82.11  5045.6   88.85  5050.6   89.75
  5054.1   89.74  5207.3   89.79  5227.3      89  5257.3   90.08  5277.3   89.25
  5307.3   90.84  5387.3   91.81  5507.3   92.22  5567.3   91.25  5597.3   92.59
  5627.3   92.61  5657.3   91.96  5677.3   93.16  5757.3   94.82  5938.6   97.32
#Mann= 4 ,-1 , 0
    4103      .1       0  4953.4     .04       0  5054.1      .1       0
  5938.6     .06       0
#XS Ineff= 2 , 0
       0 4946.73   90.99 5057.27       0   90.08
Permanent Ineff=
       F       F
Bank Sta=4953.4,5050.6
XS Rating Curve= 0
Exp/Cntr=.5,.3

Type RM Length L Ch R = 1 ,4294.   ,503,586.8,713
BEGIN DESCRIPTION:
interpolated channel - LIDAR overbanks
LOCKRIDGE DR. - XS 1
END DESCRIPTION:
XS GIS Cut Line= 5
      3101883.27     13945090.42      3101116.12     13944902.04
      3100898.98     13944927.31      3100219.66     13945188.58
      3100113.21      13945230.7
#Sta/Elev= 30
  4091.6   96.68  4121.6   95.88  4171.6   97.77  4241.6   98.07  4361.6   96.48
  4431.6   93.82  4561.6   92.33  4671.6   92.41  4761.6   90.54  4781.6   91.48
  4821.6    91.7  4931.5   90.75  4961.5   86.15  4981.5   79.95  4983.3   79.99
 4991.23   76.35 4996.62    75.9 5011.72      78  5041.5   86.18  5071.5   88.93
  5190.1   89.17  5230.1   88.41  5260.1   89.65  5280.1   88.63  5310.1   90.03
  5340.1   89.65  5490.1   92.01  5730.1    94.3  5790.1   93.64  5942.5   96.33
#Mann= 3 ,-1 , 0
  4091.6      .1       0  4931.5     .04       0  5071.5      .1       0
Bank Sta=4931.5,5071.5
XS Rating Curve= 0
Exp/Cntr=.3,.1

Type RM Length L Ch R = 1 ,3707.20 ,1220,1131.2,1088
BEGIN DESCRIPTION:
Cross Section K120-00-00-X2
END DESCRIPTION:
XS GIS Cut Line= 5
       3101707.5      13944882.5      3101374.27     13944787.46
      3101244.93     13944625.78      3101083.25     13944076.06
      3100987.97     13943924.73
#Sta/Elev= 30
  4226.1    96.5  4376.1    93.9  4526.1    92.1  4572.6      92  4612.6    91.2
  4632.6    89.6  4642.6    89.5  4662.6    90.1  4722.6      89  4779.7    88.8
  4849.2   87.99  4945.4   87.98  4984.4   79.72    4994   74.09  4995.2   72.72
  4999.5   72.83  5003.7   72.67  5005.9   74.25  5015.5   79.67  5049.3   88.73
  5079.6   88.44  5133.1   89.28  5159.7    88.7  5189.7      90  5209.7    89.8
  5219.7      90  5259.7    93.4  5352.7    96.6  5432.7    98.9  5531.5   99.83
#Mann= 5 ,-1 , 0
  4226.1      .1       0  4945.4     .04       0  5049.3    .045       0
  5079.6      .1       0  5209.7     .12       0
Bank Sta=4945.4,5049.3
XS Rating Curve= 0
Exp/Cntr=.3,.1