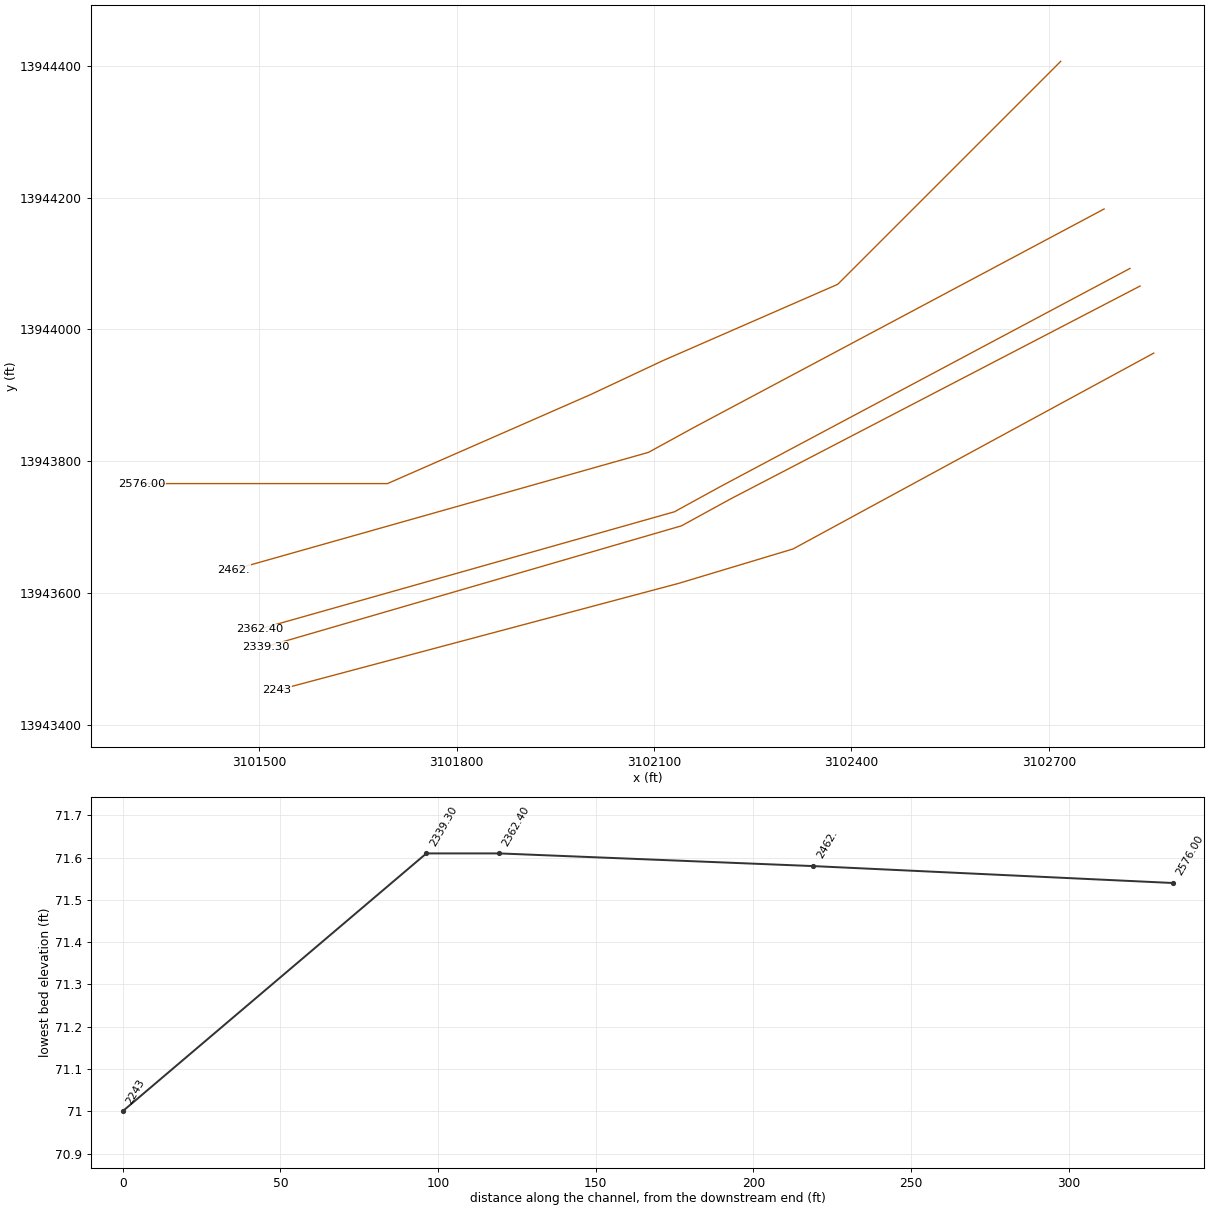
HEC-RAS study K120-00-00.prj: K120-00-00

--- K120-00-00.g01 (geometry) --- (continued)

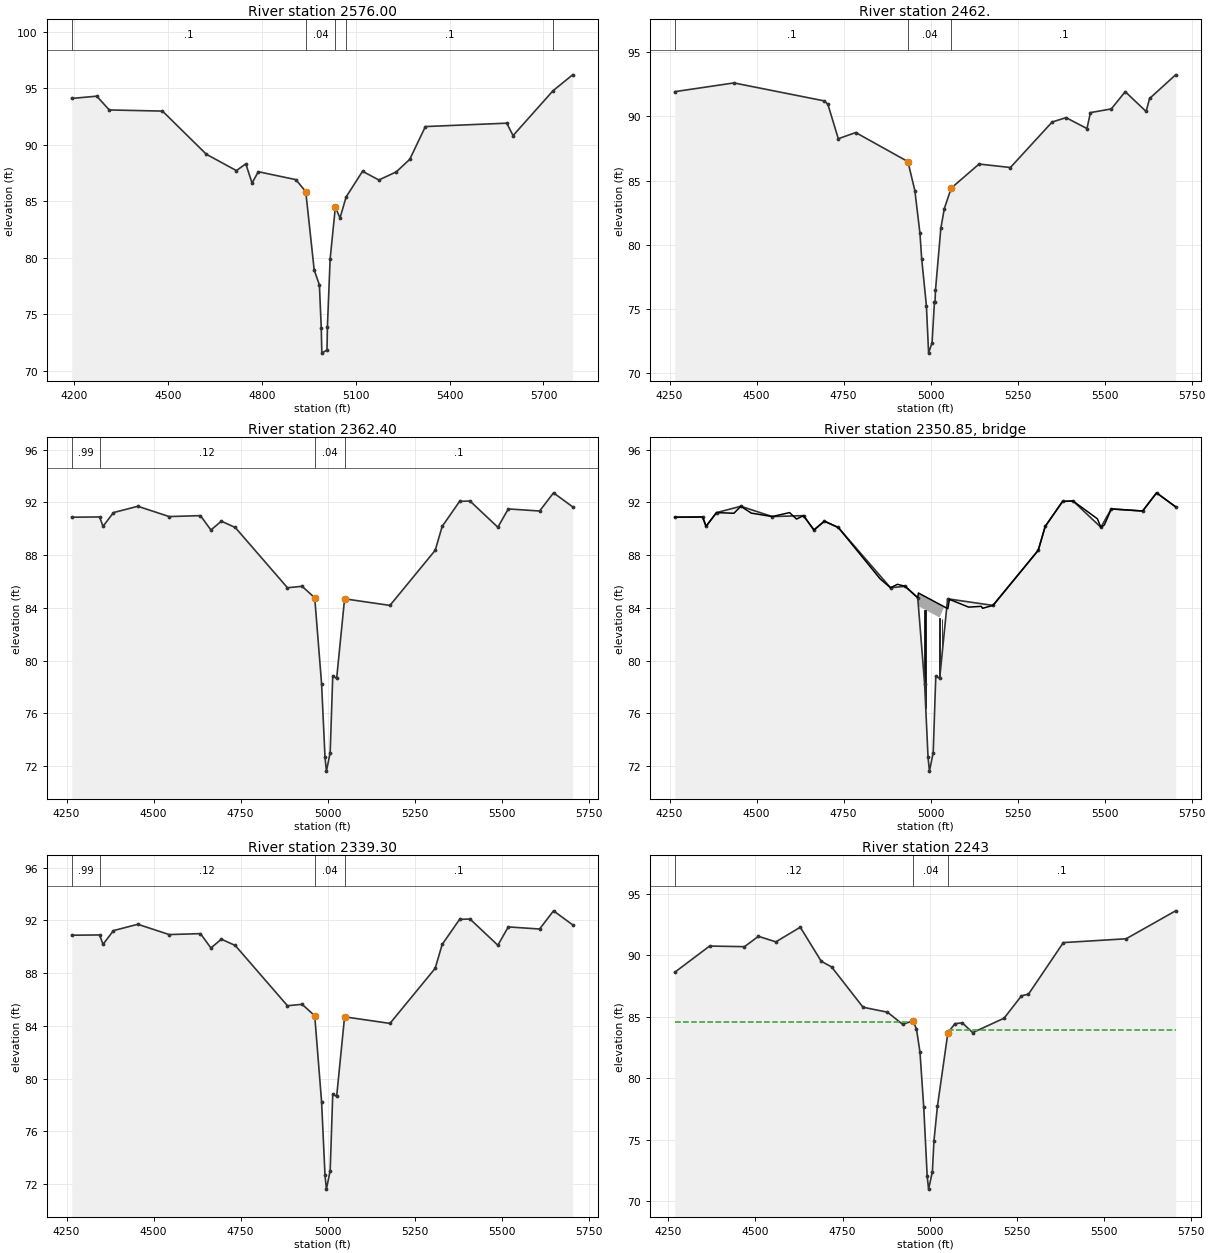
Type RM Length L Ch R = 1 ,2576.00 ,115,114,113.6
BEGIN DESCRIPTION:
Cross Section K120-00-00-X1
END DESCRIPTION:
XS GIS Cut Line= 6
      3102717.85      13944406.8      3102379.11     13944068.41
      3102113.29     13943952.48      3102003.79     13943901.13
      3101695.17     13943766.01       3101321.9     13943766.01
#Sta/Elev= 30
  4193.1   94.09  4273.1   94.29  4313.1   93.07  4483.1   92.97  4623.1   89.15
  4719.2    87.7  4749.2    88.3  4769.2    86.6  4789.2    87.6  4909.2    86.9
  4940.7   85.84  4967.7    78.9  4984.3   77.58  4990.2   73.78  4992.1   71.54
  5008.6   71.82  5009.9   73.87  5018.6   79.88  5035.3   84.47  5050.1    83.5
  5069.7   85.37  5122.1   87.64  5174.3   86.87  5230.1   87.59  5272.9    88.7
  5322.9    91.6  5582.9    91.9  5602.9    90.8  5730.5   94.77  5793.1   96.18
#Mann= 5 ,-1 , 0
  4193.1      .1       0  4940.7     .04       0  5035.3    .045       0
  5069.7      .1       0  5730.5     .99       0
Bank Sta=4940.7,5035.3
XS Rating Curve= 0
Exp/Cntr=.3,.1

Type RM Length L Ch R = 1 ,2462.   ,100,99.6,98
BEGIN DESCRIPTION:
interpolated channel - LIDAR overbanks
PL1_K120-00-00-S1a - XS 4
END DESCRIPTION:
XS GIS Cut Line= 4
      3102783.76     13944182.72      3102161.69     13943851.75
      3102091.66      13943813.4      3101461.49     13943635.42
#Sta/Elev= 30
    4265   91.92    4435    92.6    4695    91.2    4705   90.94    4735   88.26
    4785   88.74    4935   86.48    4955   84.22  4969.6   80.91 4974.61   78.91
 4988.14   75.28  4994.5   71.58 5004.43    72.4 5011.24   75.55 5012.84   75.55
 5014.28   76.49  5029.6   81.28  5039.6   82.82  5059.5   84.42  5139.5   86.29
  5229.5   86.02  5349.5   89.56  5389.5    89.9  5449.5   89.05  5459.5   90.29
  5519.5   90.58  5559.5   91.92  5619.5   90.38  5629.5   91.39  5704.3   93.23
#Mann= 3 ,-1 , 0
    4265      .1       0    4935     .04       0  5059.5      .1       0
Bank Sta=4935,5059.5
XS Rating Curve= 0
Exp/Cntr=.5,.3

Type RM Length L Ch R = 1 ,2362.40 ,23.1,23.1,23.1
BEGIN DESCRIPTION:
Upstream Section of Bridge/Culvert/Weir
PL1_K120-00-00-S1a - XS 3
END DESCRIPTION:
XS GIS Cut Line= 4
      3102823.08     13944092.51      3102201.01     13943761.54
      3102130.98     13943723.19      3101500.81     13943545.22
#Sta/Elev= 30
  4264.7   90.87  4344.7   90.89  4354.7   90.18  4384.7   91.22  4454.7    91.7
  4544.7   90.92  4634.7   90.99  4664.7    89.9  4694.7   90.57  4734.7   90.09
  4884.7   85.52  4926.7   85.63    4963   84.76  4982.7   78.24  4992.6   72.65
  4996.6   71.61  5007.4   73.01  5014.8   78.83    5026   78.64  5048.8   84.68
  5179.2   84.18  5309.2   88.36  5329.2   90.17  5379.2   92.07  5409.2    92.1
  5489.2   90.11  5519.2    91.5  5609.2   91.34  5649.2   92.72    5704   91.66
#Mann= 4 ,-1 , 0
  4264.7     .99       0  4344.7     .12       0    4963     .04       0
  5048.8      .1       0
#XS Ineff= 2 , 0
       0    4953   84.58  5058.8       0   83.96
Permanent Ineff=
       F       F
Bank Sta=4963,5048.8
XS Rating Curve= 0
Exp/Cntr=.5,.3

Type RM Length L Ch R = 3 ,2350.85 ,,,
BEGIN DESCRIPTION:
PL1_K120-00-00-S1a
END DESCRIPTION:
Bridge Culvert--1,0,-1,-1, 0
Deck Dist Width WeirC Skew NumUp NumDn MinLoCord MaxHiCord MaxSubmerge Is_Ogee
10,1,2.6,0, 40, 40, , , .95, 0, ,,,
  4264.7  4344.7  4354.7  4384.7  4434.7  4454.7  4484.7  4544.7  4594.7  4614.7
  4634.7  4664.7  4694.7  4734.7  4854.7  4884.7  4904.7  4926.7  4960.2    4963
  4964.8 4964.91    4965  5049.5  5053.9  5109.2  5145.6  5149.2  5179.2  5309.2
  5329.2  5379.2  5409.2  5479.2  5489.2  5499.2  5519.2  5609.2  5649.2    5704
   90.87   90.89   90.18   91.22   91.17    91.7   91.18   90.92   91.22   90.73
   90.99    89.9   90.57   90.09    86.2   85.52   85.78   85.63   84.83   84.77
   85.12   85.12   85.12   83.93   84.64   84.05   84.11   83.96   84.18   88.36
   90.17   92.07    92.1   90.75   90.11   90.28    91.5   91.34   92.72   91.66
   90.87   90.89   90.18   91.22   91.17    91.7   91.18   90.92   91.22   90.73
   90.99    89.9   90.57   90.09    86.2   85.52   85.78   85.63   84.83   84.76
   84.16   84.13   84.12   82.93   84.63   84.05   84.11   83.96   84.18   88.36
   90.17   92.07    92.1   90.75   90.11   90.28    91.5   91.34   92.72   91.66
  4264.7  4344.7  4354.7  4384.7  4434.7  4454.7  4484.7  4544.7  4594.7  4614.7
  4634.7  4664.7  4694.7  4734.7  4854.7  4884.7  4904.7  4926.7  4960.2    4963
  4964.8 4964.91    4965  5049.5  5053.9  5109.2  5145.6  5149.2  5179.2  5309.2
  5329.2  5379.2  5409.2  5479.2  5489.2  5499.2  5519.2  5609.2  5649.2    5704
   90.87   90.89   90.18   91.22   91.17    91.7   91.18   90.92   91.22   90.73
   90.99    89.9   90.57   90.09    86.2   85.52   85.78   85.63   84.83   84.77
   85.12   85.12   85.12   83.93   84.64   84.05   84.11   83.96   84.18   88.36
   90.17   92.07    92.1   90.75   90.11   90.28    91.5   91.34   92.72   91.66
   90.87   90.89   90.18   91.22   91.17    91.7   91.18   90.92   91.22   90.73
   90.99    89.9   90.57   90.09    86.2   85.52   85.78   85.63   84.83   84.76
   84.16   84.13   84.12   82.93   84.63   84.05   84.11   83.96   84.18   88.36
   90.17   92.07    92.1   90.75   90.11   90.28    91.5   91.34   92.72   91.66
Pier Skew, UpSta & Num, DnSta & Num=  ,4983, 2 ,4983, 2 , 0 , 0 , 0 ,,
     1.7     1.7
   76.59   84.88
     1.7     1.7
   76.59   84.88
Pier Skew, UpSta & Num, DnSta & Num=  ,4986, 2 ,4986, 2 , 0 , 0 , 0 ,,
     1.7     1.7
    74.9   84.84
     1.7     1.7
    74.9   84.84
Pier Skew, UpSta & Num, DnSta & Num=  ,5026, 2 ,5026, 2 , 0 , 0 , 0 ,,
     1.7     1.7
   77.65   84.27
     1.7     1.7
   77.65   84.27
Pier Skew, UpSta & Num, DnSta & Num=  ,5032.9, 2 ,5032.9, 2 , 0 , 0 , 0 ,,
     1.7     1.7
   78.89   84.24
     1.7     1.7
   78.89   84.24
BR Coef= 1 , 1 , 1 ,1.25, 0 ,,,.8,0,2,0,
WSPro=,,,, 1 ,,,, 0 ,,,, 0 ,,,,-1 ,-1 ,-1 , 0 , 0 , 0 , 0 , 0
BC Design=,, 0 ,, 0 ,,,,,,
BC HTab HWMax=92.72

Type RM Length L Ch R = 1 ,2339.30 ,101,96.3,87
BEGIN DESCRIPTION:
Downstream Section of Bridge/Culvert/Weir
PL1_K120-00-00-S1a - XS 2
END DESCRIPTION:
XS GIS Cut Line= 4
      3102838.35     13944065.79      3102216.11     13943742.62
      3102141.82     13943701.93      3101511.11     13943518.72
#Sta/Elev= 30
  4264.7   90.87  4344.7   90.89  4354.7   90.18  4384.7   91.22  4454.7    91.7
  4544.7   90.92  4634.7   90.99  4664.7    89.9  4694.7   90.57  4734.7   90.09
  4884.7   85.52  4926.7   85.63    4963   84.76  4982.7   78.24  4992.6   72.65
  4996.6   71.61  5007.4   73.01  5014.8   78.83    5026   78.64  5048.8   84.68
  5179.2   84.18  5309.2   88.36  5329.2   90.17  5379.2   92.07  5409.2    92.1
  5489.2   90.11  5519.2    91.5  5609.2   91.34  5649.2   92.72    5704   91.66
#Mann= 4 ,-1 , 0
  4264.7     .99       0  4344.7     .12       0    4963     .04       0
  5048.8      .1       0
#XS Ineff= 2 , 0
       0 4956.33   84.58 5055.47       0   83.96
Permanent Ineff=
       F       F
Bank Sta=4963,5048.8
XS Rating Curve= 0
Exp/Cntr=.5,.3

Type RM Length L Ch R = 1 ,2243    ,0,0,0
BEGIN DESCRIPTION:
extrapolated channel - LIDAR overbanks
PL1_K120-00-00-S1a - XS 1
END DESCRIPTION:
XS GIS Cut Line= 4
      3102859.16     13943964.02      3102311.26     13943666.82
      3102137.89      13943614.7      3101527.11      13943452.2
#Sta/Elev= 30
  4268.6   88.61  4368.6   90.74  4468.6   90.69  4508.6   91.53  4558.6   91.08
  4628.6   92.27  4688.6   89.51  4718.6   89.04  4808.6   85.77  4878.6   85.37
  4921.9   84.39  4951.9   84.66  4961.9   83.99  4971.9   82.12  4982.7   77.63
  4992.6   72.04  4996.6      71  5007.4    72.4  5011.9   74.91  5021.9   77.72
  5051.9   83.69  5071.9   84.43    5093   84.51    5123   83.71    5213   84.88
    5263    86.7    5283   86.83    5383   91.02    5563   91.33    5705    93.6
#Mann= 3 ,-1 , 0
  4268.6     .12       0  4951.9     .04       0  5051.9      .1       0
#XS Ineff= 2 , 0
       0 4956.33   84.58 5055.47       0   83.96
Permanent Ineff=
       F       F
Bank Sta=4951.9,5051.9
XS Rating Curve= 0
Exp/Cntr=.3,.1

Chan Stop Cuts=-1